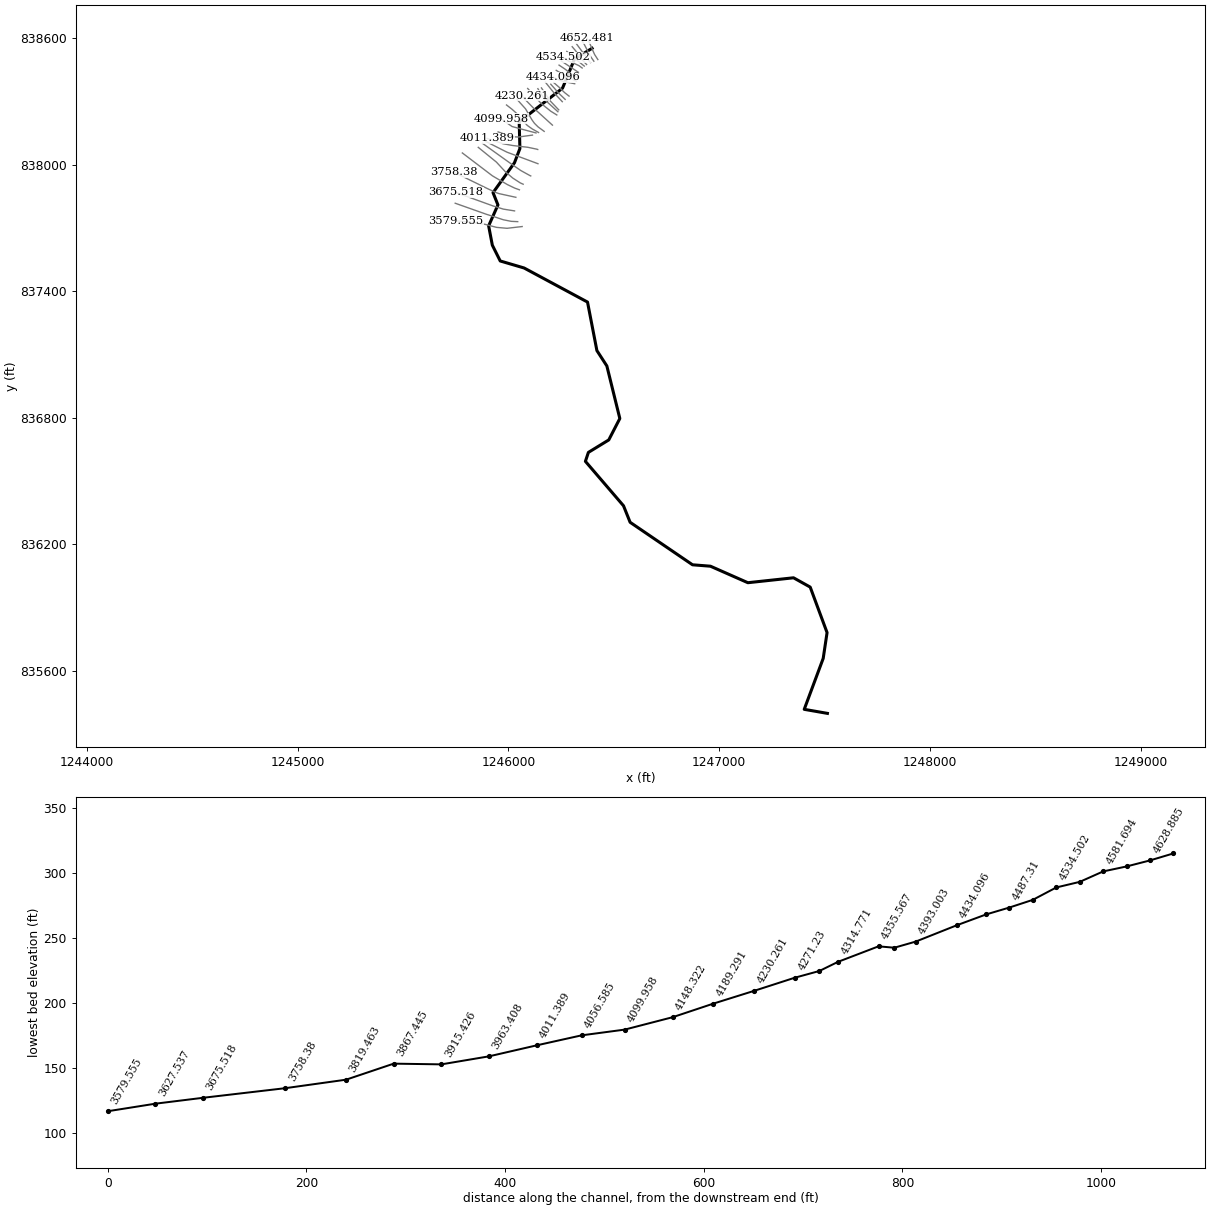
--- 84_ras.prj (project) ---

Proj Title=84
Current Plan=p01
Default Exp/Contr=0.3,0.1
English Units
Geom File=g01
Flow File=f01
Plan File=p01
Y Axis Title=Elevation
X Axis Title(PF)=Main Channel Distance
X Axis Title(XS)=Station
BEGIN DESCRIPTION:
RFD model 84 exported to HEC-RAS
END DESCRIPTION:

--- 84_ras.p01 (plan) ---

Plan Title=Plan 01
Program Version=4.10
Short Identifier=Plan 01
Geom File=g01
Flow File=f01
Subcritical Flow
Calc Critical at every XS
Secant Critical Depth

--- 84_ras.f01 (steady flow) ---

Flow Title=Flow 01
Program Version=5.01
Number of Profiles= 5
Profile Names=10yr,25yr,50yr,100yr,500yr
River Rch & RM=84,54,4652.481
  154.65   276.4  395.03  538.22  967.46
River Rch & RM=84,54,4581.694
  174.39  312.51  447.77  611.74 1107.67
River Rch & RM=84,54,4463.714
  182.39  327.17  469.22   641.7 1165.08
River Rch & RM=84,54,4355.567
   186.7  335.07  480.78  657.85 1196.09
River Rch & RM=84,54,4230.261
  194.07  348.59  500.59  685.57 1249.42
River Rch & RM=84,54,4099.958
  197.75  355.36   510.5  699.44 1276.16
River Rch & RM=84,54,3963.408
  200.21  359.86  517.11  708.69 1294.01
River Rch & RM=84,54,3867.445
  201.43  362.12  520.42  713.32 1302.95
River Rch & RM=84,54, 3758.38
  203.27   365.5  525.38  720.26 1316.36
River Rch & RM=84,54,3627.537
     285  516.27  747.38  1032.5 1926.14
River Rch & RM=84,54,3531.573
  289.25  524.13  759.01 1048.91 1958.51
River Rch & RM=84,54, 3435.61
   293.5     532  770.63 1065.33 1990.92
River Rch & RM=84,54,3243.684
  296.53  537.62  778.94 1077.06 2014.11
River Rch & RM=84,54,3147.721
  301.38   546.6  792.23 1095.84 2051.25
River Rch & RM=84,54,3051.758
  304.41  552.22  800.54 1107.58 2074.49
River Rch & RM=84,54,2955.795
  420.76  768.72 1121.99 1563.75 2987.05
River Rch & RM=84,54,2859.831
  427.36  781.04 1140.35  1589.9 3039.88
River Rch & RM=84,54,2763.274
  430.36  786.64  1148.7 1601.79 3063.91
River Rch & RM=84,54,2667.968
  473.48  867.27 1268.98 1773.35  3411.8
River Rch & RM=84,54,2473.902
  478.26  876.23 1282.36 1792.45 3450.65
River Rch & RM=84,54,2314.376
  482.44  884.06 1294.06 1809.16 3484.67
River Rch & RM=84,54,2090.049
  520.65  955.68 1401.13 1962.23 3797.04
River Rch & RM=84,54,1899.657
  527.21  967.98 1419.54 1988.58 3850.95
River Rch & RM=84,54,1696.881
  537.34     987    1448 2029.33 3934.41
River Rch & RM=84,54, 1522.21
  548.66 1008.24 1479.82  2074.9 4027.86
River Rch & RM=84,54,1331.818
  554.02 1018.31  1494.9  2096.5 4072.19
River Rch & RM=84,54,1141.426
  574.25 1056.32 1551.86 2178.17 4240.04
River Rch & RM=84,54,946.9117
     579 1065.26 1565.27  2197.4 4279.61
River Rch & RM=84,54,760.6421
  827.88 1535.15 2272.72 3216.48 6401.92
River Rch & RM=84,54,533.0212
  844.94 1567.47 2321.57 3287.13 6550.65
River Rch & RM=84,54,112.9292
  857.87 1591.99 2358.63 3340.76 6663.67
River Rch & RM=84,54,       0
  863.16 1602.02  2373.8 3362.71 6709.95
Boundary for River Rch & Prof#=84,54,1
Up Type= 0
Dn Type= 2
Boundary for River Rch & Prof#=84,54,2
Up Type= 0
Dn Type= 2
Boundary for River Rch & Prof#=84,54,2
Up Type= 0
Dn Type= 2
Boundary for River Rch & Prof#=84,54,2
Up Type= 0
Dn Type= 2
Boundary for River Rch & Prof#=84,54,2
Up Type= 0
Dn Type= 2

--- 84_ras.g01 (geometry) ---

Geom Title=84
Program Version=4.10

River Reach=84,54
Reach XY= 30
1246397.13413912838552.9160262051246313.80082875838502.082710356
1246256.87081128838363.5886679141246051.30089712838203.749472842
1246054.63422573838077.0828435121246028.80089805 838009.58286421
1245927.13425705837867.9162423911245950.46758181837809.582925603
1245906.30092523837710.4162895381245923.80091739 837618.74964945
1245961.30090421837543.7496705061246074.63420326837510.416343689
1246375.46744353837348.7497160141246420.00738534837118.536584571
1246467.22960752837045.619917899 1246528.8007156836796.249874756
1246476.30072802 836694.583239661246379.63408801836635.416593343
 1246365.4674243836592.9166062921246546.30069831836382.083329961
1246577.70993164836303.7290035641246873.80059394836102.083403111
1246958.80056876836095.4167359321247136.30051434836017.083420545
1247352.96711805836040.4167406111247432.13376015835996.250084698
1247512.13373032835780.4168127781247493.80039883835657.916849509
1247403.80041817835416.2502569111247513.80038527835397.083592698

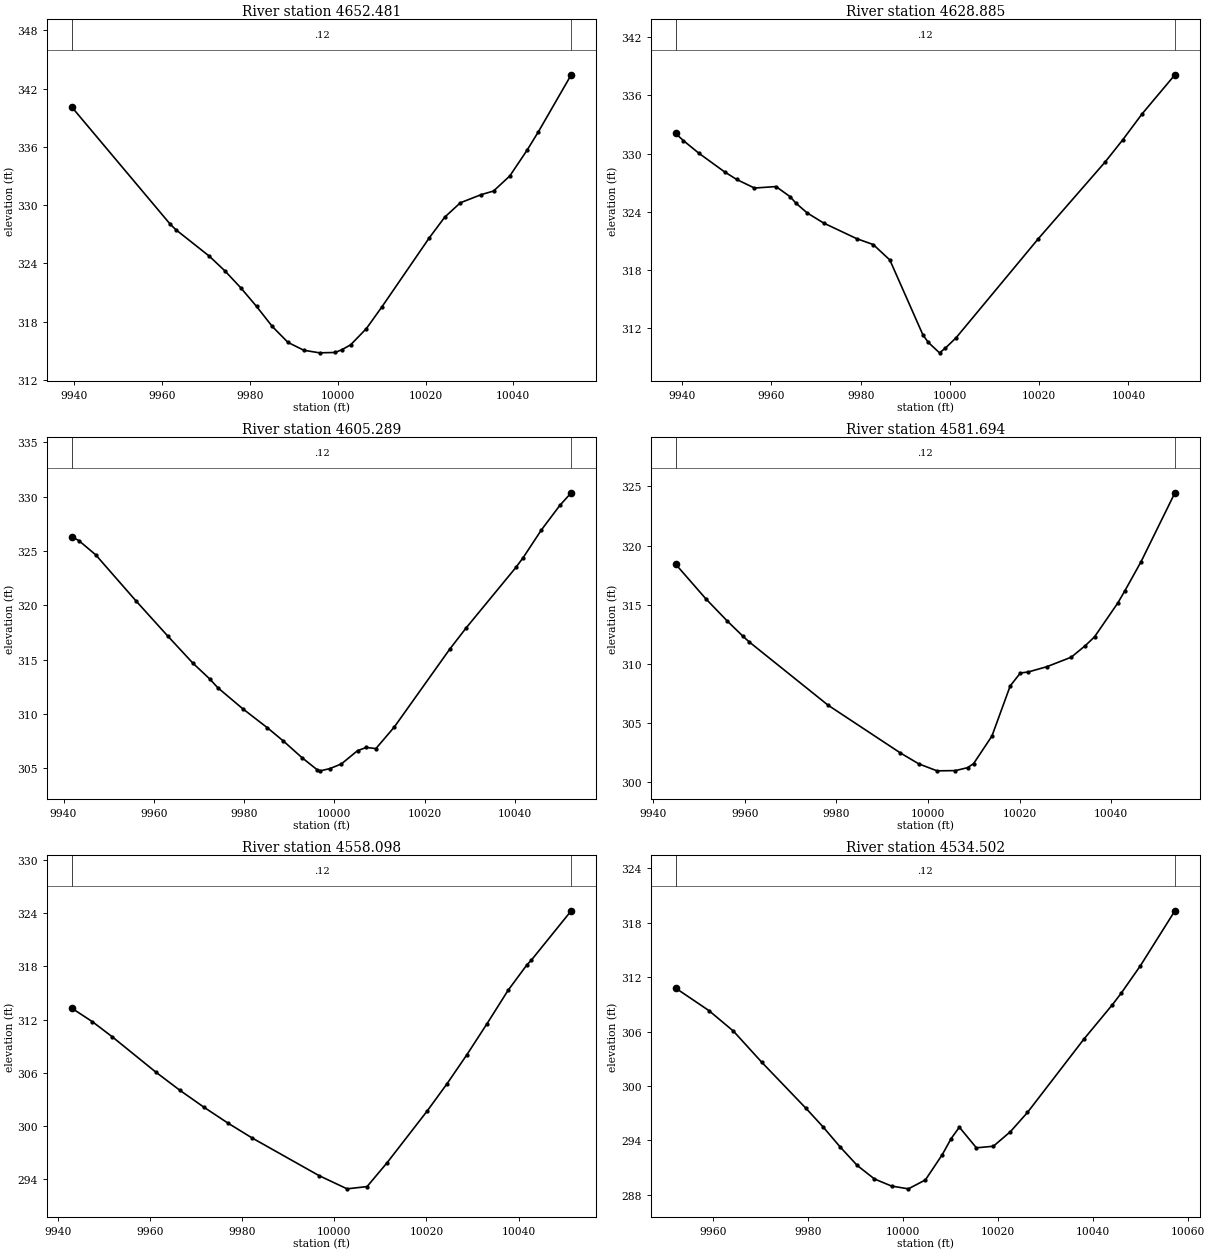
Type RM Length L Ch R = 1 ,4652.481,23.595900,23.595900,23.595900
XS GIS Cut Line= 6
1246424.59412622838499.3224266021246408.85738832838523.822913855
1246396.53197116838551.6364193411246395.85453224838553.518194214
1246385.00109035838578.9653972541246372.60915154838600.133806795
#Sta/Elev= 25
9939.459340.07349961.852328.03129963.125327.47049970.737324.74879974.325323.2211
9977.914321.48959981.502319.57879985.091317.51039988.679315.86879992.268315.0623
9995.857314.79569999.432314.8347   10001315.130110002.96315.627610006.53317.2924
 10010.1319.5488 10020.8326.594710024.36328.752910027.93330.2399 10032.7331.0815
10035.49331.447210039.19332.996710043.09335.621910045.68337.524310053.19343.4137
#Mann= 3 , 0 , 0
9939.459    0.12       09939.459    0.12       010053.19    0.12       0
#XS Ineff= 2 , 0
       09985.033                       0
Bank Sta=9939.459,10053.19
Exp/Cntr=0.3,0.1

Type RM Length L Ch R = 1 ,4628.885,23.595800,23.595800,23.595800
XS GIS Cut Line= 6
1246405.60624287838491.5797945261246390.24358889838513.782659411
1246374.60018384838543.384203553 1246373.6644085838545.151779413
1246359.76913878838572.0249246951246349.48464778838588.212284014
#Sta/Elev= 24
 9938.52 332.0739940.232331.34829943.716330.03689949.482328.10899952.201327.3228
9956.191326.43659961.014326.5906 9964.17325.54629965.519324.85849967.975 323.877
9971.686 322.8229979.108321.20689982.818320.59619986.529319.00269993.951311.2592
9995.142310.49269997.662309.4116    9999309.909510001.37310.964410019.84321.2193
10034.79329.130810038.68331.388910043.06334.094110050.43 338.139
#Mann= 3 , 0 , 0
 9938.52    0.12       0 9938.52    0.12       010050.43    0.12       0
#XS Ineff= 2 , 0
       0 9990.27                       0
Bank Sta=9938.52,10050.43
Exp/Cntr=0.3,0.1

Type RM Length L Ch R = 1 ,4605.289,23.595900,23.595900,23.595900
XS GIS Cut Line= 5
 1246389.5687536838485.2597127851246381.61754891838494.998225287
 1246355.0350768838530.7742834841246353.76366237838532.318143994
1246323.20646021838573.751818791
#Sta/Elev= 27
9941.857326.32569943.364325.97439947.112324.66319956.013320.43589963.172317.1468
9968.673314.68329972.362313.24789974.174 312.4319979.675310.50519985.176308.7407
9988.711307.52319992.799306.00599996.178304.88719996.886304.7833    9999304.9888
10001.55305.418210005.13306.637510007.08306.9383 10009.2306.829510013.28308.8151
10025.51315.949510029.19317.931110040.24323.508810041.82324.394710045.89326.9608
10049.97329.212810052.48330.3677
#Mann= 3 , 0 , 0
9941.857    0.12       09941.857    0.12       010052.48    0.12       0
#XS Ineff= 2 , 0
       09985.943        10008.35       0
Bank Sta=9941.857,10052.48
Exp/Cntr=0.3,0.1

Type RM Length L Ch R = 1 ,4581.694,23.595900,23.595900,23.595900
XS GIS Cut Line= 6
1246371.11547235 838475.893266411246348.01157302838499.851929531
1246335.95611641838516.7780222451246334.82305878838518.426106155
 1246319.3873826838540.7073151021246302.74176452838560.407077178
#Sta/Elev= 24
9944.936318.42599951.498 315.5129956.224313.61289959.569312.35589960.951 311.867
 9978.22306.50069993.961302.47389997.989 301.54710001.98300.955410005.98300.9747
10008.64301.222310009.97301.572610013.96303.893910017.95308.134910020.16309.2249
10021.94309.319410025.93309.757210031.27310.563610034.36 311.54710036.35312.2833
10041.43315.145110042.95316.160910046.52318.6475 10053.9 324.464
#Mann= 3 , 0 , 0
9944.936    0.12       09944.936    0.12       0 10053.9    0.12       0
#XS Ineff= 2 , 0
       0                10010.44       0
Bank Sta=9944.936,10053.9
Exp/Cntr=0.3,0.1

Type RM Length L Ch R = 1 ,4558.098,23.595800,23.595800,23.595800
XS GIS Cut Line= 5
1246360.17767337838468.4105699361246318.54381868838502.131873146
1246316.82204136838503.6897092311246315.40782782838505.103922844
1246277.26832396838538.039469182
#Sta/Elev= 20
9943.101313.27889947.553311.76599951.775 310.097  9961.3306.08549966.513 304.038
9971.725302.13329976.938300.33929982.151298.67279996.678294.424510002.77292.9298
10007.11 293.18310011.44295.865110020.11301.678910024.45304.774110028.78308.0645
10033.12311.539410037.68315.296510041.78318.1806 10042.7318.683610051.39324.2742
#Mann= 3 , 0 , 0
9943.101    0.12       09943.101    0.12       010051.39    0.12       0
#XS Ineff= 2 , 0
       0                10012.82       0
Bank Sta=9943.101,10051.39
Exp/Cntr=0.3,0.1

Type RM Length L Ch R = 1 ,4534.502,23.595900,23.595900,23.595900
XS GIS Cut Line= 6
1246350.14545217838459.3507282581246334.64327049838470.650442362
1246309.51858756838482.1192245631246307.63510379838482.791897416
1246284.73773998838492.7204931231246258.81368077838510.172516704
#Sta/Elev= 24
9952.198310.78779959.176308.31569964.364306.03679970.315 302.6059979.574297.5449
 9983.18295.48929986.787293.26899990.393291.2198    9994289.73179997.606288.9472
10001.14288.640310004.72289.620810008.29292.423610010.14294.187510011.87295.4423
10015.45293.166210019.02293.3406 10022.6294.9458 10026.2297.072610038.06305.1604
10044.06308.956410045.97310.274310049.93 313.24510057.21319.3218
#Mann= 3 , 0 , 0
9952.198    0.12       09952.198    0.12       010057.21    0.12       0
#XS Ineff= 2 , 0
       0                 10013.4       0
Bank Sta=9952.198,10057.21
Exp/Cntr=0.3,0.1

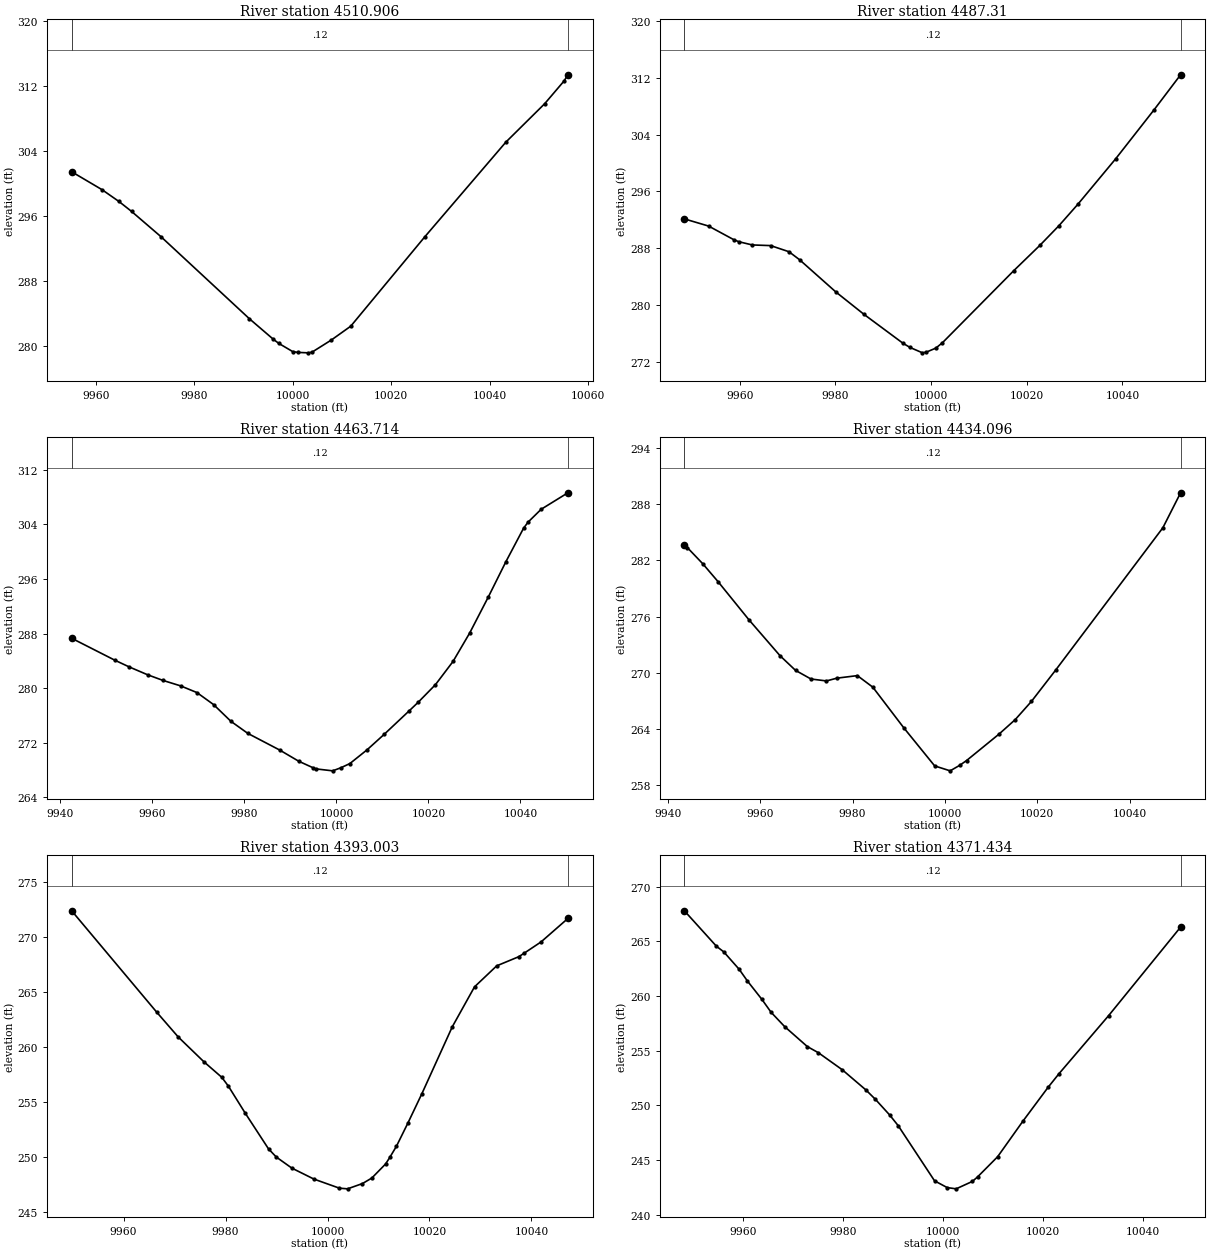
Type RM Length L Ch R = 1 ,4510.906,23.595900,23.595900,23.595900
XS GIS Cut Line= 4
1246335.23037222838437.1101026541246298.48475051838461.171797812
 1246296.8078633 838462.261774571246251.06977361838492.664552689
#Sta/Elev= 19
9955.077 301.4459961.256299.23329964.687297.78169967.245 296.5619973.234293.4395
9991.201283.33059996.061280.8034 9997.19280.2875 9999.98279.2929   10001279.1881
10003.17279.133210003.91279.214110007.85280.714510011.79282.416210026.87 293.452
10043.31305.095510051.19 309.82310055.13312.624610055.92313.3941
#Mann= 3 , 0 , 0
9955.077    0.12       09955.077    0.12       010055.92    0.12       0
#XS Ineff= 2 , 0
       0                10018.45       0
Bank Sta=9955.077,10055.92
Exp/Cntr=0.3,0.1

Type RM Length L Ch R = 1 , 4487.31,23.595900,23.595900,23.595900
XS GIS Cut Line= 6
1246326.21959305838414.9037074741246299.11106023838431.307178274
  1246283.897387838442.515420064 1246282.3554635838443.789183006
1246268.66534141838454.1724292641246240.43570688838473.092707962
#Sta/Elev= 23
9948.418292.1103 9953.49291.09649958.788289.16639959.827288.88979962.622288.4374
9966.457 288.3469970.292287.48179972.502286.35729980.103281.80719985.977278.6568
9994.127 274.5869995.594273.99729998.202 273.236    9999273.333610000.98273.8979
10002.38274.661110017.27284.800810022.77288.394910026.72291.141810030.67294.1537
10038.57300.556110046.65307.504410052.17312.4147
#Mann= 3 , 0 , 0
9948.418    0.12       09948.418    0.12       010052.17    0.12       0
#XS Ineff= 2 , 0
       0                               0
Bank Sta=9948.418,10052.17
Exp/Cntr=0.3,0.1

Type RM Length L Ch R = 1 ,4463.714,29.618400,29.618400,29.618400
XS GIS Cut Line= 5
1246321.89850628838396.8605873141246271.57886821838422.710173458
 1246269.8264364838423.6740110071246251.53551373838433.490049154
1246227.05925968838448.258402318
#Sta/Elev= 30
9942.429287.31169951.762284.11549954.922 283.1199958.942281.96299962.299281.1328
9966.122280.33589969.675279.35359973.302277.58879977.052275.14899980.741273.3736
9987.662270.93729991.806269.29789994.842268.36539995.494  268.189999.185267.8901
   10001268.351310002.92268.952810006.64270.954110010.37273.225110015.76 276.638
10017.81277.953910021.54280.516910025.36283.916110028.97288.064910033.03293.3562
10036.86298.532910040.69303.419910041.67304.319510044.52306.204910050.34308.6232
#Mann= 3 , 0 , 0
9942.429    0.12       09942.429    0.12       010050.34    0.12       0
#XS Ineff= 2 , 0
       0                               0
Bank Sta=9942.429,10050.34
Exp/Cntr=0.3,0.1

Type RM Length L Ch R = 1 ,4434.096,41.092500,41.092500,41.092500
XS GIS Cut Line= 5
1246314.68331128838384.6824178991246258.25026974838396.189758629
1246256.43214008838397.0230681151246231.17855349838406.623063415
1246212.54868793838415.968646511
#Sta/Elev= 23
9943.588283.62759944.216283.37039947.565281.64279950.913 279.712 9957.61275.6354
9964.306271.82489967.655 270.2659971.003269.34099974.352269.13619976.621269.4324
9981.048269.70269984.397 268.4699991.093264.1385 9997.79260.068710001.14259.5439
10003.18260.1237 10004.7260.643910011.72 263.46210015.23265.009410018.74266.9515
10023.96270.2764 10047.2285.476710051.04289.2097
#Mann= 3 , 0 , 0
9943.588    0.12       09943.588    0.12       010051.04    0.12       0
#XS Ineff= 2 , 0
       0                               0
Bank Sta=9943.588,10051.04
Exp/Cntr=0.3,0.1

Type RM Length L Ch R = 1 ,4393.003,21.569800,21.569800,21.569800
XS GIS Cut Line= 6
1246287.86039457838326.0886679141246266.55348361 838342.79871802
1246251.91111359838357.0584156661246250.61922917838358.585188285
1246241.28726044838367.4713003041246214.94372794838390.411584586
#Sta/Elev= 27
9949.818272.34039966.547263.09999970.716260.87439975.715258.63699979.268257.2048
9980.554256.40579983.847253.96039988.427250.70549989.959249.96079993.006248.9563
9997.335247.959310002.33247.133810003.93247.073310006.86247.554510008.69248.0556
10011.39249.331810012.22249.933510013.51250.935210015.77253.0547 10018.5255.7097
10024.47261.797310028.83265.425710033.18267.335510037.53268.170610038.49268.4622
10041.88269.508910047.15271.6427
#Mann= 3 , 0 , 0
9949.818    0.12       09949.818    0.12       010047.15    0.12       0
#XS Ineff= 2 , 0
       0                               0
Bank Sta=9949.818,10047.15
Exp/Cntr=0.3,0.1

Type RM Length L Ch R = 1 ,4371.434,15.866100,15.866100,15.866100
XS GIS Cut Line= 5
1246269.49214152838310.3659913991246236.79433542838341.725881383
1246217.50026676838364.2637974621246216.08605328838365.678011075
1246201.21191701838382.369329527
#Sta/Elev= 26
9948.281267.80289954.706264.55679956.165264.04539959.252262.44959960.905261.3795
9963.798259.70099965.644258.51619968.344257.2134 9972.89255.38369975.124254.8138
9979.864253.26859984.604251.42099986.527250.55259989.343249.13949991.073248.1537
9998.358243.101910000.89242.483810002.68242.368510005.93243.0471   10007243.4728
10010.98245.302810016.02248.542210021.07251.645710023.25252.890210033.18258.1995
10047.61266.3107
#Mann= 3 , 0 , 0
9948.281    0.12       09948.281    0.12       010047.61    0.12       0
#XS Ineff= 2 , 0
       0                               0
Bank Sta=9948.281,10047.61
Exp/Cntr=0.3,0.1

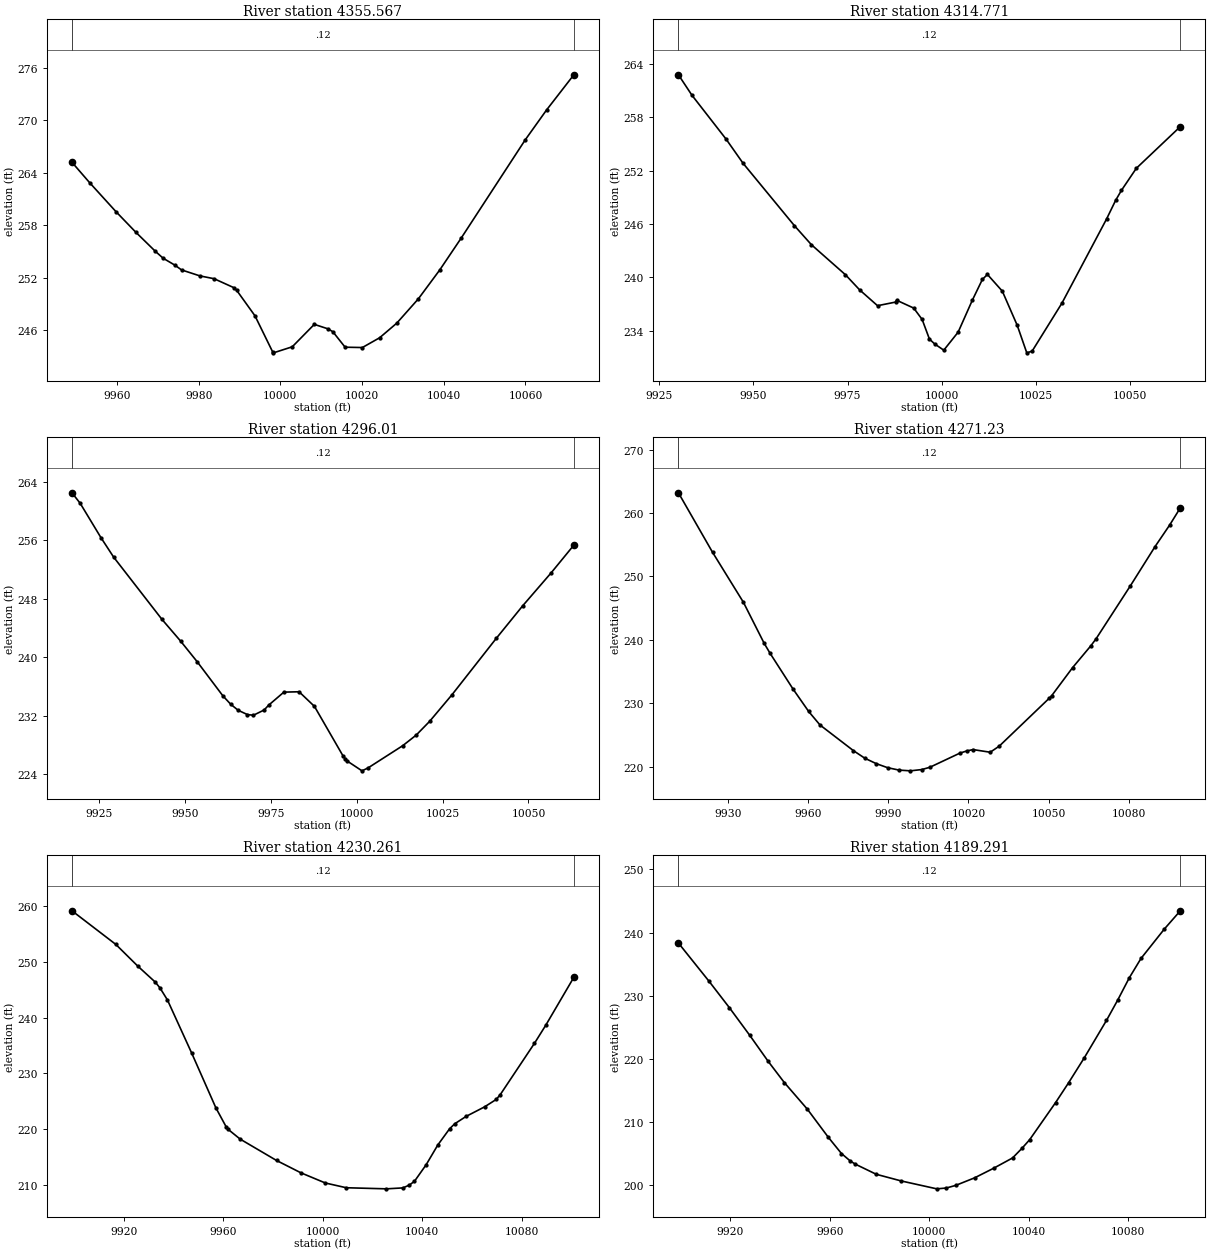
Type RM Length L Ch R = 1 ,4355.567,40.796700,40.796700,40.796700
XS GIS Cut Line= 4
 1246255.8291446838299.5261679141246225.09997791838332.338667914
 1246215.2041446838342.7553345711246175.36039457838392.234501243
#Sta/Elev= 29
9948.986265.21629953.334262.87279959.781259.5608 9964.58257.2358 9969.38255.0437
9971.314254.2419 9974.18253.45289975.809252.90899980.304252.22449983.779251.9025
9988.579250.88659989.294250.58489993.789247.65829998.146243.50219998.313243.4269
10002.91244.117410008.31246.682810011.64246.173910012.84245.845610015.85 244.071
10020.07 244.03310024.28245.145310028.49246.818810033.77249.5965   10039252.8946
10044.23256.522910059.92267.766910065.15271.189710071.84275.2199
#Mann= 3 , 0 , 0
9948.986    0.12       09948.986    0.12       010071.84    0.12       0
#XS Ineff= 2 , 0
       0                               0
Bank Sta=9948.986,10071.84
Exp/Cntr=0.3,0.1

Type RM Length L Ch R = 1 ,4314.771,18.761200,18.761200,18.761200
XS GIS Cut Line= 4
1246238.90206128838260.7240845711246194.37081128838307.599084601
1246187.59997791838319.0574178991246156.87081128838364.890751258
#Sta/Elev= 30
9930.144262.78379933.739260.48089942.789255.55029947.315252.82269960.891245.8327
9965.416243.68199974.466240.29679978.206238.60559982.969236.82179987.733237.2273
9988.042237.43339992.568236.5535  9994.8235.27629996.731233.0725 9998.13232.5187
10000.54231.820410004.35233.848910008.11237.433610010.78239.776410012.12240.3343
10016.07238.457210020.02234.618710022.56231.522110023.97231.708710031.87237.0981
10043.72246.565810046.13248.666210047.67249.788110051.62252.270210063.29256.9568
#Mann= 3 , 0 , 0
9930.144    0.12       09930.144    0.12       010063.29    0.12       0
#XS Ineff= 2 , 0
       0                               0
Bank Sta=9930.144,10063.29
Exp/Cntr=0.3,0.1

Type RM Length L Ch R = 1 , 4296.01,24.779600,24.779600,24.779600
XS GIS Cut Line= 6
1246234.99581128838251.8699178991246193.58956125838289.630334586
1246176.66247794838304.9949178991246171.97041148838310.625397697
1246158.74382961838331.1596287341246139.94372794838361.244917899
#Sta/Elev= 30
9917.081 262.5199919.482261.07729925.513256.3928 9929.22253.72159943.274245.2164
9948.696242.24989953.564 239.4049961.035234.74499963.302233.60389965.475 232.777
9968.171232.18879969.916232.1002 9973.04232.81929974.353233.47829978.784235.2598
9983.215235.30989987.684233.3115 9995.98226.5573 9996.59226.18049997.264225.8246
10001.53224.496910003.31224.902510013.39227.9373 10017.3229.3808 10021.2 231.254
10027.73 234.901 10040.6242.600310048.34247.078310056.57 251.55410063.21255.3617
#Mann= 3 , 0 , 0
9917.081    0.12       09917.081    0.12       010063.21    0.12       0
#XS Ineff= 2 , 0
       09989.125        10018.97       0
Bank Sta=9917.081,10063.21
Exp/Cntr=0.3,0.1

Type RM Length L Ch R = 1 , 4271.23,40.969400,40.969400,40.969400
XS GIS Cut Line= 6
1246229.77724057838236.5281967371246200.64096043838254.620015636
1246179.15810293838272.059985995 1246177.4841637838273.154484764
1246154.28017771838292.4317270821246091.58279613 838362.22264117
#Sta/Elev= 30
  9911.4263.18839924.177253.80339935.762245.89759943.486239.46399945.696237.8875
 9954.31 232.2369960.181228.69139964.407 226.5649976.943222.51059981.208221.3165
9985.473220.46459989.739219.82489994.004219.44569998.269219.327510002.53219.5299
10005.53219.885210016.81 222.12210019.34222.457410021.72222.680210028.16222.2634
10031.54223.222510050.21230.755610051.17231.176210059.03235.6185 10065.9239.0802
10067.85240.187910080.63248.5004 10089.9254.709410095.36258.098410099.35260.8096
#Mann= 3 , 0 , 0
  9911.4    0.12       0  9911.4    0.12       010099.35    0.12       0
#XS Ineff= 2 , 0
       09986.228        10018.39       0
Bank Sta=9911.4,10099.35
Exp/Cntr=0.3,0.1

Type RM Length L Ch R = 1 ,4230.261,40.969300,40.969300,40.969300
XS GIS Cut Line= 5
1246209.03068688838188.2714985051246135.05837693838255.512040432
1246133.38443774838256.6065392081246119.20917133838269.107125698
1246062.61579193  838327.1768151
#Sta/Elev= 30
9899.034259.21429916.702 253.1639925.569249.24929932.581246.38599934.436245.3595
9937.459243.18649947.214233.63659956.969223.77489961.039220.42179961.847219.9378
9966.725218.17449981.357214.33539991.113212.1285   10001210.287410009.43209.4347
10025.58209.237910032.16209.404610034.74209.900710036.86210.596210041.56  213.57
10046.26217.128810050.96220.014210053.06220.932110057.64222.259310065.06223.9693
10069.76225.310310071.39226.178810085.13235.387210089.71238.659210100.99247.2596
#Mann= 3 , 0 , 0
9899.034    0.12       09899.034    0.12       010100.99    0.12       0
#XS Ineff= 2 , 0
       09983.203        10030.54       0
Bank Sta=9899.034,10100.99
Exp/Cntr=0.3,0.1

Type RM Length L Ch R = 1 ,4189.291,40.969400,40.969400,40.969400
XS GIS Cut Line= 6
1246169.84254838838158.6521005761246140.72796674838180.035862329
1246123.58273916838197.0853493711246112.29120242838212.718514083
1246081.40316638838265.5932109171246040.56380796838310.861295473
#Sta/Elev= 30
9899.071238.34129911.446232.25989919.588228.10119927.729223.75059935.194219.6076
9941.653216.26819950.959212.03569959.374207.59479964.642205.03599968.243203.8342
9970.245203.34819978.658201.74649988.683200.693510002.97199.445910006.78199.5738
10010.59199.990510018.21201.188910025.84202.702810033.46 204.33310037.27205.8677
10040.34207.224810050.75213.084610055.96216.205510062.34220.199310071.22226.0872
 10075.8229.351310080.41232.838110085.11235.896510094.52240.560510100.93243.4428
#Mann= 3 , 0 , 0
9899.071    0.12       09899.071    0.12       010100.93    0.12       0
#XS Ineff= 2 , 0
       0                10030.78       0
Bank Sta=9899.071,10100.93
Exp/Cntr=0.3,0.1

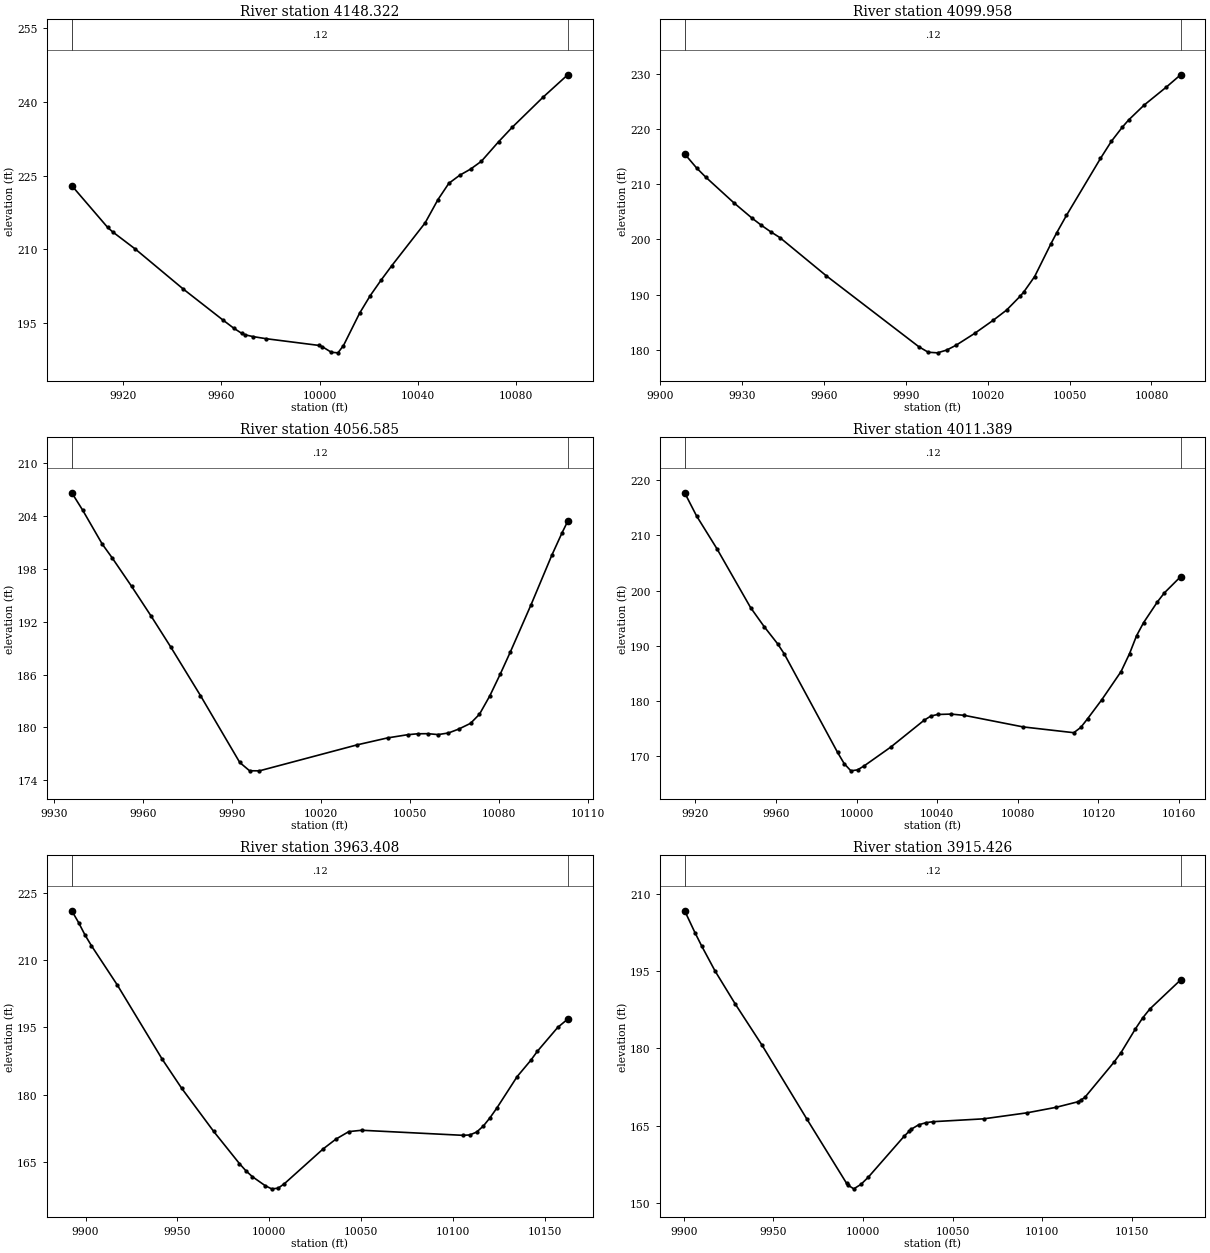
Type RM Length L Ch R = 1 ,4148.322,48.363900,48.363900,48.363900
XS GIS Cut Line= 6
1246143.08967464838153.440863809 1246112.8225548838170.466165944
1246089.66072521838186.8944691781246038.56257053838244.456650571
1246018.01550471838262.9557036351245991.14283748 838283.97009796
#Sta/Elev= 30
9899.051222.94539913.679214.45899915.743213.54839924.972 210.057 9944.48201.9495
9960.569195.68879964.947194.04049968.228192.98089969.562192.68489972.893192.3115
9978.207191.88769999.764190.5208   10001190.277310004.73189.135610007.41189.0205
10009.67190.504510016.19197.029710020.57 200.63810024.96203.764910029.34206.7121
10042.89 215.37710048.15220.132910052.56223.418610056.98225.054510061.39226.2986
10065.81227.892910072.78231.837410078.36234.788410090.85240.862710100.96245.4442
#Mann= 3 , 0 , 0
9899.051    0.12       09899.051    0.12       010100.96    0.12       0
#XS Ineff= 2 , 0
       0                               0
Bank Sta=9899.051,10100.96
Exp/Cntr=0.3,0.1

Type RM Length L Ch R = 1 ,4099.958,43.372600,43.372600,43.372600
XS GIS Cut Line= 4
1246131.25293503838151.1983356211246070.83626837 838167.17055783
1246017.36404616838181.7538911581245965.28071279838218.559446711
#Sta/Elev= 30
9908.992215.4936 9913.33 212.9719916.723211.28449926.904206.69139933.691203.8579
9937.084202.57629940.478201.40579943.872200.34579960.839193.44029994.824180.5645
9998.224179.585310001.62179.474210005.03179.983510008.43180.852410015.23182.9946
10022.03 185.37110026.91187.208210031.82189.6841 10033.2190.471310037.21193.2888
10043.19199.238610045.25201.175710048.88 204.37410061.32214.667410065.33217.7817
10069.35220.347910071.62221.6308 10077.3224.327810085.42227.580210090.69229.8248
#Mann= 3 , 0 , 0
9908.992    0.12       09908.992    0.12       010090.69    0.12       0
#XS Ineff= 2 , 0
       0                10027.94       0
Bank Sta=9908.992,10090.69
Exp/Cntr=0.3,0.1

Type RM Length L Ch R = 1 ,4056.585,45.196000,45.196000,45.196000
XS GIS Cut Line= 6
1246114.27791047838140.9371452481246081.12020397838136.471960068
1246049.09023064838131.9417348211246024.81785989838132.787163273
1245996.69285989838140.0788299441245951.38035986838156.224663273
#Sta/Elev= 28
 9935.85206.65279939.505204.68939946.126200.82429949.436199.27819956.057196.0082
9962.678192.60879969.307189.09059979.245183.61919992.496176.01899995.809175.0752
9999.122175.067510032.17178.026610042.34 178.80810049.11179.1708 10052.5179.2772
10055.92179.2877 10059.4179.186210062.88179.368910066.37179.814910070.32180.4632
10073.33181.492810076.82183.5817 10080.3186.024710083.78188.594710090.75193.9492
10097.71199.5389 10101.2202.1163 10103.1203.4179
#Mann= 3 , 0 , 0
 9935.85    0.12       0 9935.85    0.12       0 10103.1    0.12       0
#XS Ineff= 2 , 0
       0                10040.77       0
Bank Sta=9935.85,10103.1
Exp/Cntr=0.3,0.1

Type RM Length L Ch R = 1 ,4011.389,47.981600,47.981600,47.981600
XS GIS Cut Line= 6
1246139.25528544838072.7181447741246134.00633842 838074.36341317
1246092.87859184 838083.062648521246021.12783712838091.507487625
1245973.72801444 838100.247834371245899.62254736838125.090404019
#Sta/Elev= 30
9914.699217.69149920.593213.50949930.653207.6031 9947.42196.91719954.127193.4925
9960.834190.37469964.159188.52719990.592170.72579993.896168.6835  9997.2167.3954
 10000.5167.5718 10003.8168.295710016.98 171.69210033.53 176.54510036.86177.2994
 10040.2177.589110046.87177.660610053.54177.429410082.68  175.3410107.82174.2939
10111.28175.245610114.74176.855710121.66 180.22910131.28185.3562 10135.5188.6068
10138.96191.820510142.42  194.1810149.34197.9694 10152.8 199.59410160.84202.5171
#Mann= 3 , 0 , 0
9914.699    0.12       09914.699    0.12       010160.84    0.12       0
#XS Ineff= 2 , 0
       0                 10042.7       0
Bank Sta=9914.699,10160.84
Exp/Cntr=0.3,0.1

Type RM Length L Ch R = 1 ,3963.408,47.981600,47.981600,47.981600
XS GIS Cut Line= 5
1246140.36793551838005.2076672461246040.61394095838042.439779282
1246038.72319502838043.0917607251245993.27169669838059.955209345
1245892.52619317838110.912163273
#Sta/Elev= 30
9892.524221.04799896.224218.42249899.725215.63629903.227 213.2459917.235 204.514
9941.748187.89469952.254181.44979969.764171.76389983.771164.58169987.273162.9826
9990.775161.67389997.779159.658810001.26158.953610004.76159.087910008.26160.1176
10029.26167.854510036.26  170.0610043.25171.732110050.29172.035710105.44170.9011
10109.12  170.99 10112.8171.632410116.47 172.97810120.15174.860510123.83177.0089
10134.86184.019810142.21187.617710145.89189.686410156.92194.996510162.38196.8627
#Mann= 3 , 0 , 0
9892.524    0.12       09892.524    0.12       010162.38    0.12       0
#XS Ineff= 2 , 0
       0                10040.37       0
Bank Sta=9892.524,10162.38
Exp/Cntr=0.3,0.1

Type RM Length L Ch R = 1 ,3915.426,47.981600,47.981600,47.981600
XS GIS Cut Line= 6
1246105.97795793837947.2756970971246103.14909548837948.443912134
1246058.56710416837973.0823539641246021.92625558837998.430047736
1245995.44949174838017.1822136791245876.90119317838102.057996616
#Sta/Elev= 30
9900.448 206.6649906.178202.43749909.926199.84989917.423 194.9899928.669188.6092
9943.663180.59739968.676166.29089990.843153.84079991.743 153.4749994.832152.7868
9998.822153.654410002.86 155.01610022.95162.983710025.91164.000910026.97164.3517
10030.98165.185610035.02165.594310039.05165.7994 10067.3166.351110091.51167.5157
10107.65168.576910119.75169.642710121.76170.038210123.79170.507710139.93177.2731
10143.96179.175410152.03183.790810156.07185.9053 10160.1187.648210177.24193.2674
#Mann= 3 , 0 , 0
9900.448    0.12       09900.448    0.12       010177.24    0.12       0
#XS Ineff= 2 , 0
       0                10035.55       0
Bank Sta=9900.448,10177.24
Exp/Cntr=0.3,0.1

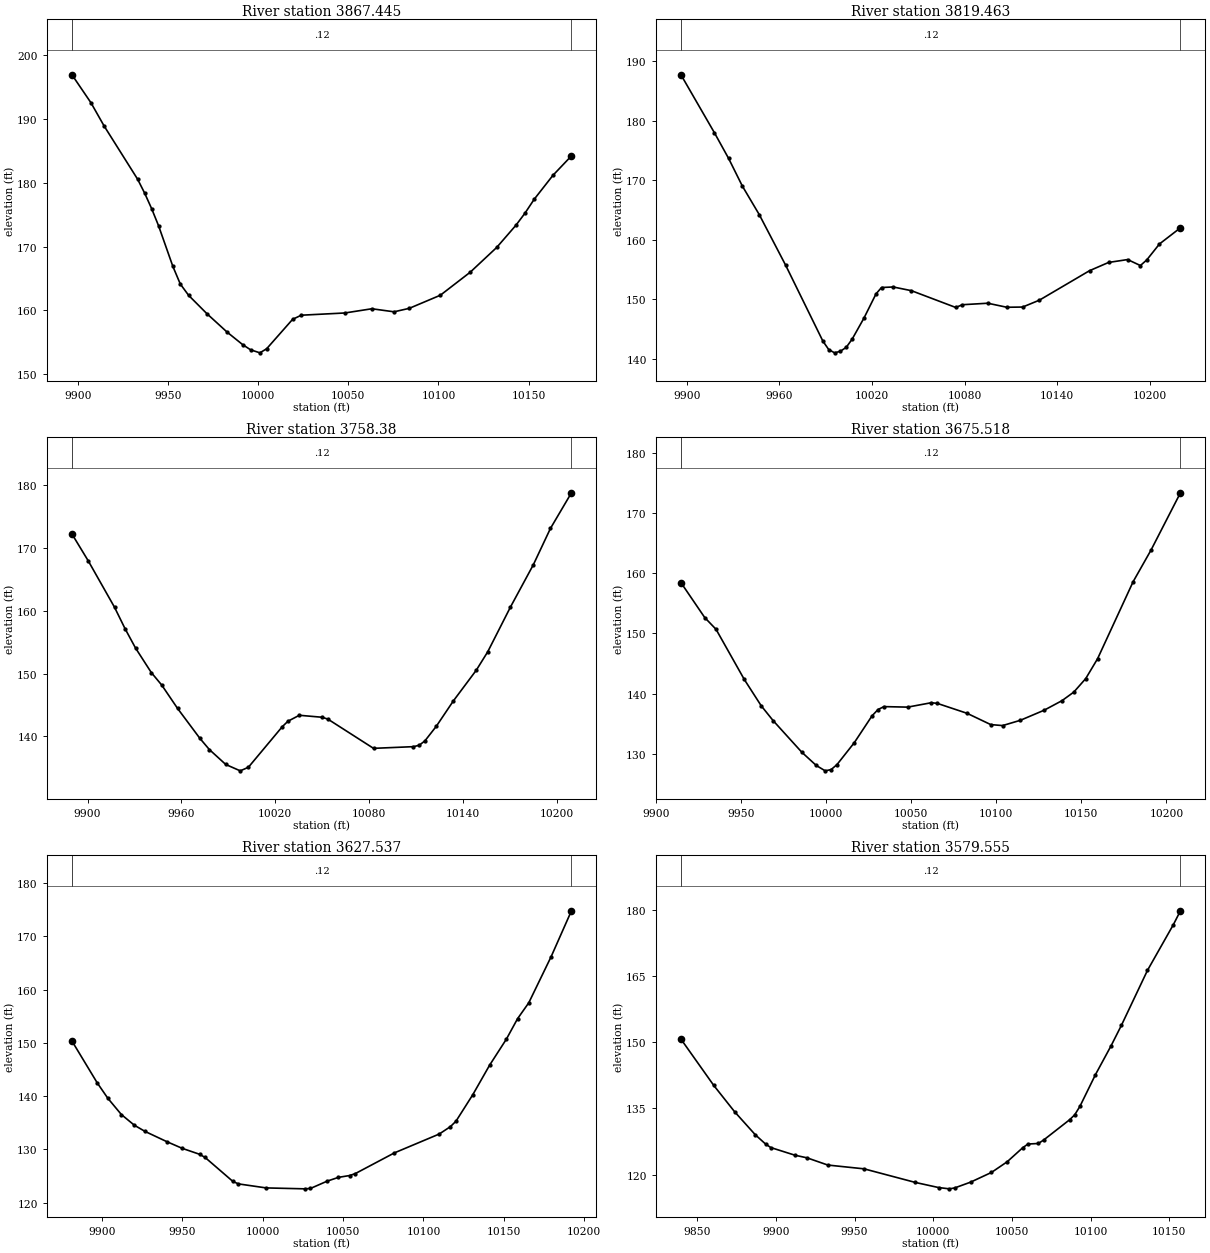
Type RM Length L Ch R = 1 ,3867.445,47.981500,47.981500,47.981500
XS GIS Cut Line= 6
1246070.16809005837907.9412092271246056.12823793837914.279633179
1246020.62616137837937.1907161181245985.26184472837967.471708849
1245943.04702654838012.9954966161245857.10952652838082.787163273
#Sta/Elev= 30
9896.783196.95079907.329192.55889914.552188.95179933.195180.57269937.099178.3865
9941.004175.93589944.804173.28039952.718166.91879956.859164.13939961.521162.3463
9971.583 159.4949982.825156.5922 9991.48154.62289995.808153.8257   10001153.3413
10004.75153.979710019.15158.596110023.96159.243410048.14159.593210063.09160.2547
 10075.4159.777310083.85160.319610101.09162.376810117.66165.989810132.31169.8626
10143.02173.358510147.93175.211210153.13177.425910163.54181.185310173.79184.2313
#Mann= 3 , 0 , 0
9896.783    0.12       09896.783    0.12       010173.79    0.12       0
#XS Ineff= 2 , 0
       0                10024.69       0
Bank Sta=9896.783,10173.79
Exp/Cntr=0.3,0.1

Type RM Length L Ch R = 1 ,3819.463,61.082900,61.082900,61.082900
XS GIS Cut Line= 6
1246052.32174709837881.4004940691246029.87470302837889.553696394
1245995.24403858837906.2230688481245960.20278397837926.577091172
1245924.54785028837947.497735992 1245781.5886932838056.224663273
#Sta/Elev= 30
9896.161187.71089917.871177.97069927.057173.66759935.983169.01599946.907164.2403
9964.005155.74919988.156142.9983 9991.95141.57489995.744141.0224 9999.54  141.29
10003.34141.955310007.15143.326910014.76146.838610022.61150.920410026.17151.9928
10033.78152.079710045.59151.4577 10074.3  148.6410078.57149.101710095.05149.3528
10107.42148.674210117.66148.711610128.49149.8638   10161154.812410173.37 156.201
10185.74156.684210193.98155.6787 10198.1156.615210206.35159.302110219.95162.0171
#Mann= 3 , 0 , 0
9896.161    0.12       09896.161    0.12       010219.95    0.12       0
#XS Ineff= 2 , 0
       0                10030.45       0
Bank Sta=9896.161,10219.95
Exp/Cntr=0.3,0.1

Type RM Length L Ch R = 1 , 3758.38,82.861900,82.861900,82.861900
XS GIS Cut Line= 6
1246035.54674518 837845.822521211245955.63149449837863.309823826
1245941.68611282837868.1321538981245930.04025066 837873.70489575
1245903.87073058837885.627872065 1245740.9636932837965.078829944
#Sta/Elev= 30
 9890.03172.21819900.464167.93679917.256160.55519923.973  157.15 9930.69154.0621
9940.765150.16149947.482148.15359957.558144.45099971.836139.68539977.906137.8979
9988.403135.51949997.662134.506210002.89 135.07710024.55141.534410028.16142.4021
10035.46143.354210050.06143.037210053.71 142.74210082.91138.087510108.46138.3569
10112.11 138.57710115.76139.272110123.06141.597110133.97145.637910148.62150.5224
10155.92 153.44310170.52160.597910185.12167.315910196.07173.102310209.51178.7824
#Mann= 3 , 0 , 0
 9890.03    0.12       0 9890.03    0.12       010209.51    0.12       0
#XS Ineff= 2 , 0
       0                10035.42       0
Bank Sta=9890.03,10209.51
Exp/Cntr=0.3,0.1

Type RM Length L Ch R = 1 ,3675.518,47.981500,47.981500,47.981500
XS GIS Cut Line= 6
1246029.32730231837781.3267321441245975.84431559837789.842340112
1245946.97807497837798.902152672 1245945.1397849837799.689991325
 1245928.6510703837804.3376729791245749.88296402837869.014015138
#Sta/Elev= 30
9914.589158.46969928.579152.64699935.223150.69159951.834142.3379  9961.8137.9464
9968.745135.49739985.627 130.2259994.156128.01239999.396127.120610002.88127.3333
10006.29128.149110016.51131.815110026.94136.285610030.43 137.32510033.92137.8171
10047.87137.732310061.83138.468510065.32138.352910082.76136.706910096.72134.8218
 10103.7134.660110114.16 135.54210128.12137.218910138.59138.805610145.56140.2405
10152.54142.479210159.52145.790610180.45158.636210190.92163.875110208.24173.4323
#Mann= 3 , 0 , 0
9914.589    0.12       09914.589    0.12       010208.24    0.12       0
#XS Ineff= 2 , 0
       09970.974           10031       0
Bank Sta=9914.589,10208.24
Exp/Cntr=0.3,0.1

Type RM Length L Ch R = 1 ,3627.537,47.981600,47.981600,47.981600
XS GIS Cut Line= 6
1246044.30560556837730.3457667681246013.62539682837731.779181406
1245976.56669509837739.1002370721245930.05067071837754.457688764
1245896.93911302837764.8292463421245747.73452652837817.682996616
#Sta/Elev= 30
9881.516150.35479897.209142.5058 9903.78  139.629912.239136.5468 9920.35 134.531
9927.038133.36419940.415131.46539950.014130.20429960.827129.08499964.282128.4871
9981.557123.98069985.012123.520410002.23122.765410026.33122.592110029.78122.6642
10040.18124.041110047.14 124.746 10054.1125.092410057.58 125.44610081.94129.3449
10109.79132.883210116.75134.271910120.23135.300410130.67140.270810141.11145.8111
10151.56 150.71610158.52154.561610165.48157.5404 10179.4166.2204   10192174.8225
#Mann= 3 , 0 , 0
9881.516    0.12       09881.516    0.12       0   10192    0.12       0
#XS Ineff= 2 , 0
       0 9962.53        10030.83       0
Bank Sta=9881.516,10192
Exp/Cntr=0.3,0.1

Type RM Length L Ch R = 1 ,3579.555,47.981600,47.981600,47.981600
XS GIS Cut Line= 6
1246065.41958022837707.1065142151245993.61156204837698.750923887
1245943.82655069837703.1727189871245888.67771965837717.727023602
1245852.13913724837723.2141519931245751.90119317837734.349663287
#Sta/Elev= 30
9839.725150.70989860.553140.22989873.788134.27249886.995129.02789893.562126.9221
9896.845126.14059912.195124.40649919.853 123.8149933.028122.18119956.084121.3224
9988.716118.2371 10003.4117.086810010.22116.792210013.63116.994310023.73118.3047
   10037120.503710046.96122.9109 10056.9126.110910060.21126.939510066.81127.0677
10070.11127.833410086.61132.426510089.92133.559310093.22135.477110103.12142.6804
10113.02149.196410119.62153.859310136.13 166.27510152.63176.664810157.09179.7821
#Mann= 3 , 0 , 0
9839.725    0.12       09839.725    0.12       010157.09    0.12       0
#XS Ineff= 2 , 0
       09956.239        10034.78       0
Bank Sta=9839.725,10157.09
Exp/Cntr=0.3,0.1