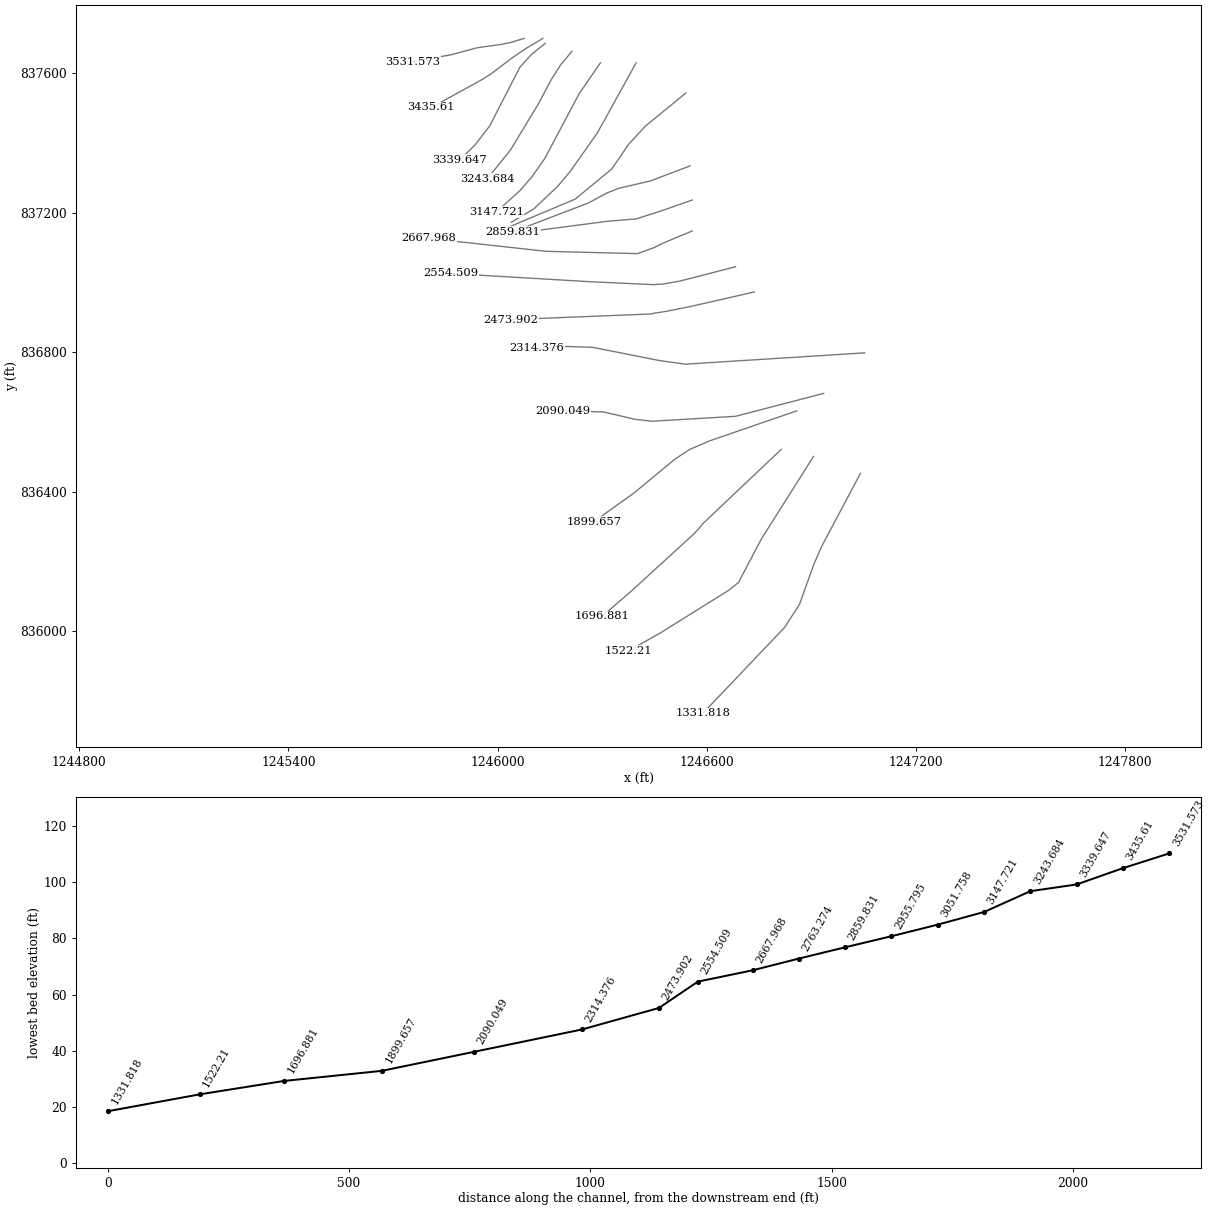
HEC-RAS study 84_ras.prj: 84

--- 84_ras.g01 (geometry) --- (continued)

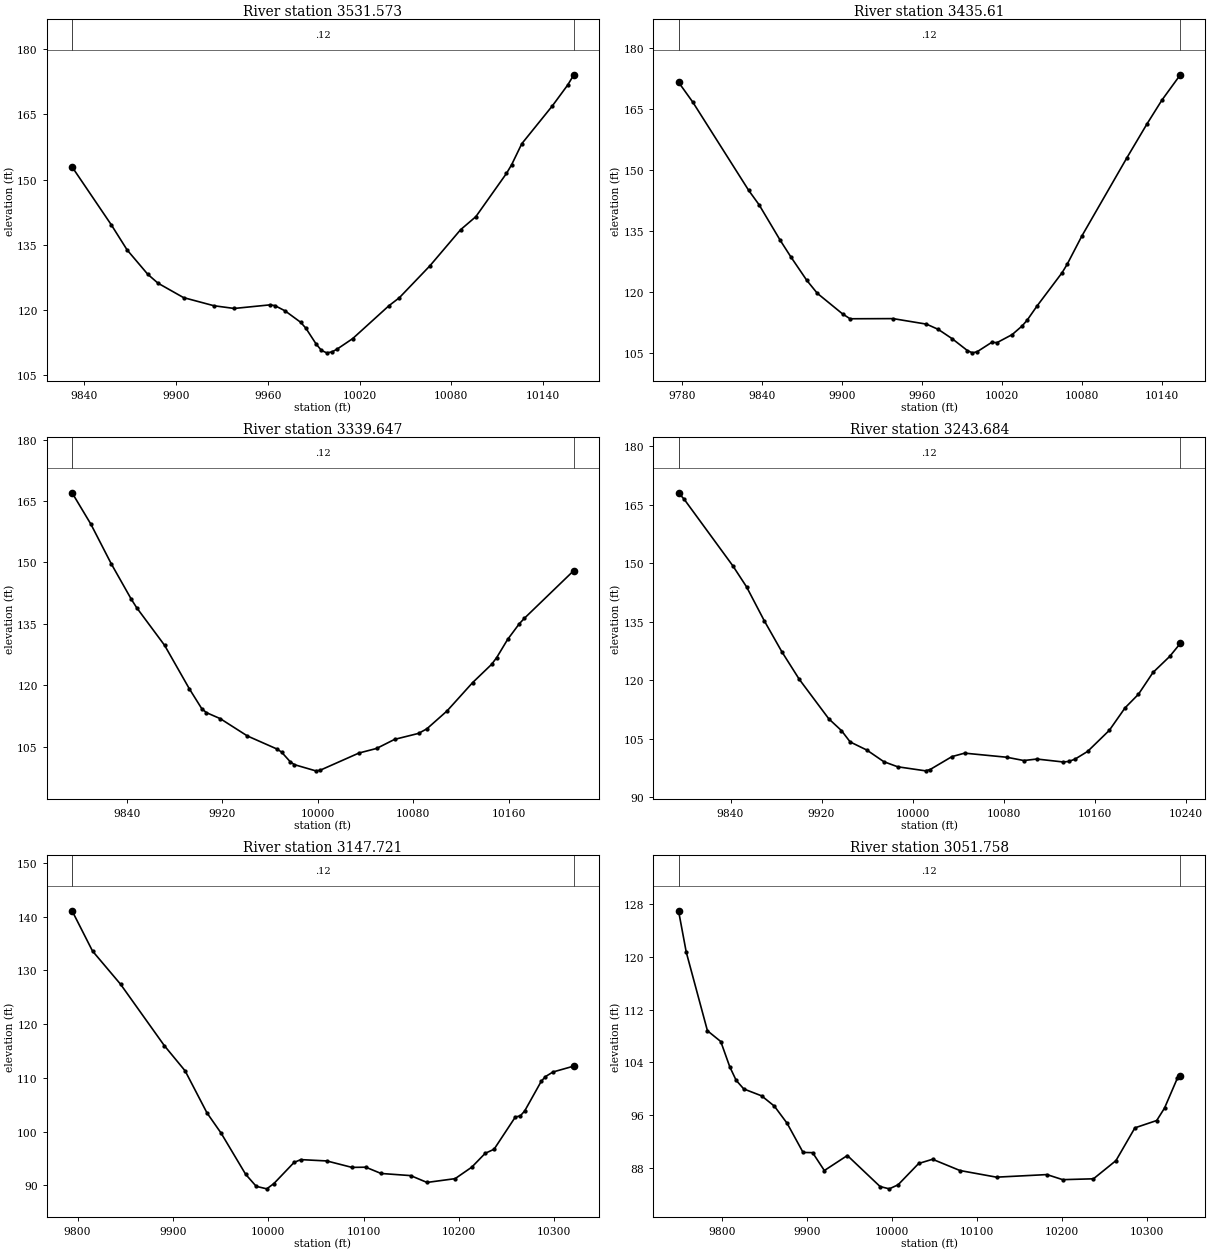
Type RM Length L Ch R = 1 ,3531.573,95.963100,95.963100,95.963100
XS GIS Cut Line= 6
1246076.14705941837700.7494895011246038.15469763837689.049343109
1246007.14756456837682.8390005381245942.65597552837673.960551217
1245867.56038532837653.895214304 1245755.6438826837633.574794233
#Sta/Elev= 30
9832.101152.93919857.786139.59259868.084133.83749881.564128.24429888.256126.1936
 9904.97122.87289924.841 121.0029938.088120.3795 9961.27121.20039964.582121.0482
9971.278119.83379981.485117.20429984.887115.84559991.692112.15689995.094110.7364
9998.496110.170810001.94110.381410005.33111.0289 10015.5113.442110039.22121.0155
10045.99122.8416   10066130.196410086.01138.485210096.02141.498310116.02 151.442
10119.36153.418110126.03158.272210146.03166.985410156.04171.775110160.06174.1266
#Mann= 3 , 0 , 0
9832.101    0.12       09832.101    0.12       010160.06    0.12       0
#XS Ineff= 2 , 0
       09964.399        10044.08       0
Bank Sta=9832.101,10160.06
Exp/Cntr=0.3,0.1

Type RM Length L Ch R = 1 , 3435.61,95.963200,95.963200,95.963200
XS GIS Cut Line= 6
1246129.74389076837700.527456254 1246082.2523486837672.432363495
1246038.64702928837642.5894597171245979.76480895837597.837592691
1245957.92685241837583.8857155141245809.82840055837502.405436113
#Sta/Elev= 30
9777.121 171.6259787.863166.70259829.795144.98619837.638141.42559853.541132.6545
9861.492128.58799873.419122.8266 9881.37119.6114 9900.31114.54569905.957113.3372
9938.264113.37529963.398112.01269972.246110.72049982.864108.37939994.174105.4872
9997.916104.941310001.49105.224410012.26107.496910016.49 107.47910027.74109.4344
10035.24111.568210038.99112.983410046.49116.504210065.24124.684610068.99126.7142
10080.24133.807710113.99 153.03310128.98161.317610140.23 167.20910154.08173.4584
#Mann= 3 , 0 , 0
9777.121    0.12       09777.121    0.12       010154.08    0.12       0
#XS Ineff= 2 , 0
       09949.873                       0
Bank Sta=9777.121,10154.08
Exp/Cntr=0.3,0.1

Type RM Length L Ch R = 1 ,3339.647,95.963100,95.963100,95.963100
XS GIS Cut Line= 6
1246136.08265683837686.0095266251246096.50674433837653.986722767
1246063.73535863837617.9277836081245976.90927485837448.966845125
1245935.21230805837395.2034146641245891.13288197837351.622046545
#Sta/Elev= 30
9794.277167.01979810.093159.32079826.985149.73929843.866141.03259848.401138.9551
9871.789129.76349892.404119.19859902.825114.33569906.712113.35749918.374111.8767
9941.058107.65559966.077 104.4349969.651103.72189976.799 101.4019980.373100.6516
9998.24399.1389210001.7899.2594710034.51103.488610049.26104.606410064.34106.8215
10084.34108.2769 10091.3109.387710108.22113.756110129.58120.658310145.56125.1381
10149.84126.801910158.94131.211110168.69135.026110172.94136.368210214.42148.0416
#Mann= 3 , 0 , 0
9794.277    0.12       09794.277    0.12       010214.42    0.12       0
#XS Ineff= 2 , 0
       09938.873        10052.47       0
Bank Sta=9794.277,10214.42
Exp/Cntr=0.3,0.1

Type RM Length L Ch R = 1 ,3243.684,95.963200,95.963200,95.963200
XS GIS Cut Line= 6
1246213.17896807837663.5498432821246180.52760786837624.499230906
1246154.41503122837583.3220021871246116.85814664837512.756681532
1246036.27468839837379.5998548871245969.93721804837297.591692433
#Sta/Elev= 30
9794.271168.08129799.346 166.3769842.111149.30139854.047  143.969869.586135.2803
9885.126127.28669900.374120.2502 9926.39110.08769937.539107.06539945.173104.1577
9959.839102.07189974.78299.089019986.959 97.785110011.4196.7443910015.4697.08147
10034.69100.3989 10045.8101.283710082.83100.232810097.8399.3890710109.3299.77155
10132.4399.0189510137.2499.1474410142.8199.7383610153.96101.728210173.02107.1383
10186.84112.898310198.63116.392710211.41121.977610226.16126.110710235.45129.4471
#Mann= 3 , 0 , 0
9794.271    0.12       09794.271    0.12       010235.45    0.12       0
#XS Ineff= 2 , 0
       0                10037.36       0
Bank Sta=9794.271,10235.45
Exp/Cntr=0.3,0.1

Type RM Length L Ch R = 1 ,3147.721,95.963100,95.963100,95.963100
XS GIS Cut Line= 6
1246294.82230109837630.6773033291246233.06882206837540.761998326
1246135.21644017837356.1209026131246098.53266361837303.867516413
 1246063.6288507837263.8888889551245996.03350517837202.522919565
#Sta/Elev= 30
9794.216141.10349815.656133.61399845.134127.4225 9890.97116.01549912.857111.3031
9935.774103.48299950.53299.733989976.35992.053479987.428 89.81689998.49689.34985
10005.9290.32331 10027.194.2557410034.1694.78887 10061.594.5414910087.8593.34205
 10102.493.3769810118.3992.2120710149.4891.8116810166.6190.5411310196.1391.24619
10213.5593.37867 10227.7 95.9633   1023796.7189510259.28 102.71510264.51102.9295
10269.09103.8385 10286.5109.367810290.81110.230810298.78111.096810320.71112.1981
#Mann= 3 , 0 , 0
9794.216    0.12       09794.216    0.12       010320.71    0.12       0
#XS Ineff= 2 , 0
       09954.062        10035.41       0
Bank Sta=9794.216,10320.71
Exp/Cntr=0.3,0.1

Type RM Length L Ch R = 1 ,3051.758,95.963200,95.963200,95.963200
XS GIS Cut Line= 6
1246397.21224642837630.342140123 1246285.0550172 837427.92239894
1246206.34163234 837316.730075941246172.14941821  837276.3263859
 1246103.9587234 837211.746115581246038.88035986837172.995496601
#Sta/Elev= 30
9748.813126.98279757.902120.70829782.813108.80559798.518107.17039809.069103.3537
9816.571101.30039825.59699.985739846.57798.94175 9861.5897.382389876.58394.78176
9895.33790.36952 9906.59 90.33419920.36787.624649947.44489.903749985.97885.19995
9996.78584.8529810007.1385.4636810031.3688.6942410047.7189.3331410079.95  87.627
10122.9486.6213410182.2687.0127910200.8286.2440410237.0486.3738310263.4989.12868
10285.7994.0942910311.4495.2045910320.6197.0833110335.88101.652910339.23 101.925
#Mann= 3 , 0 , 0
9748.813    0.12       09748.813    0.12       010339.23    0.12       0
#XS Ineff= 2 , 0
       09943.778        10039.57       0
Bank Sta=9748.813,10339.23
Exp/Cntr=0.3,0.1

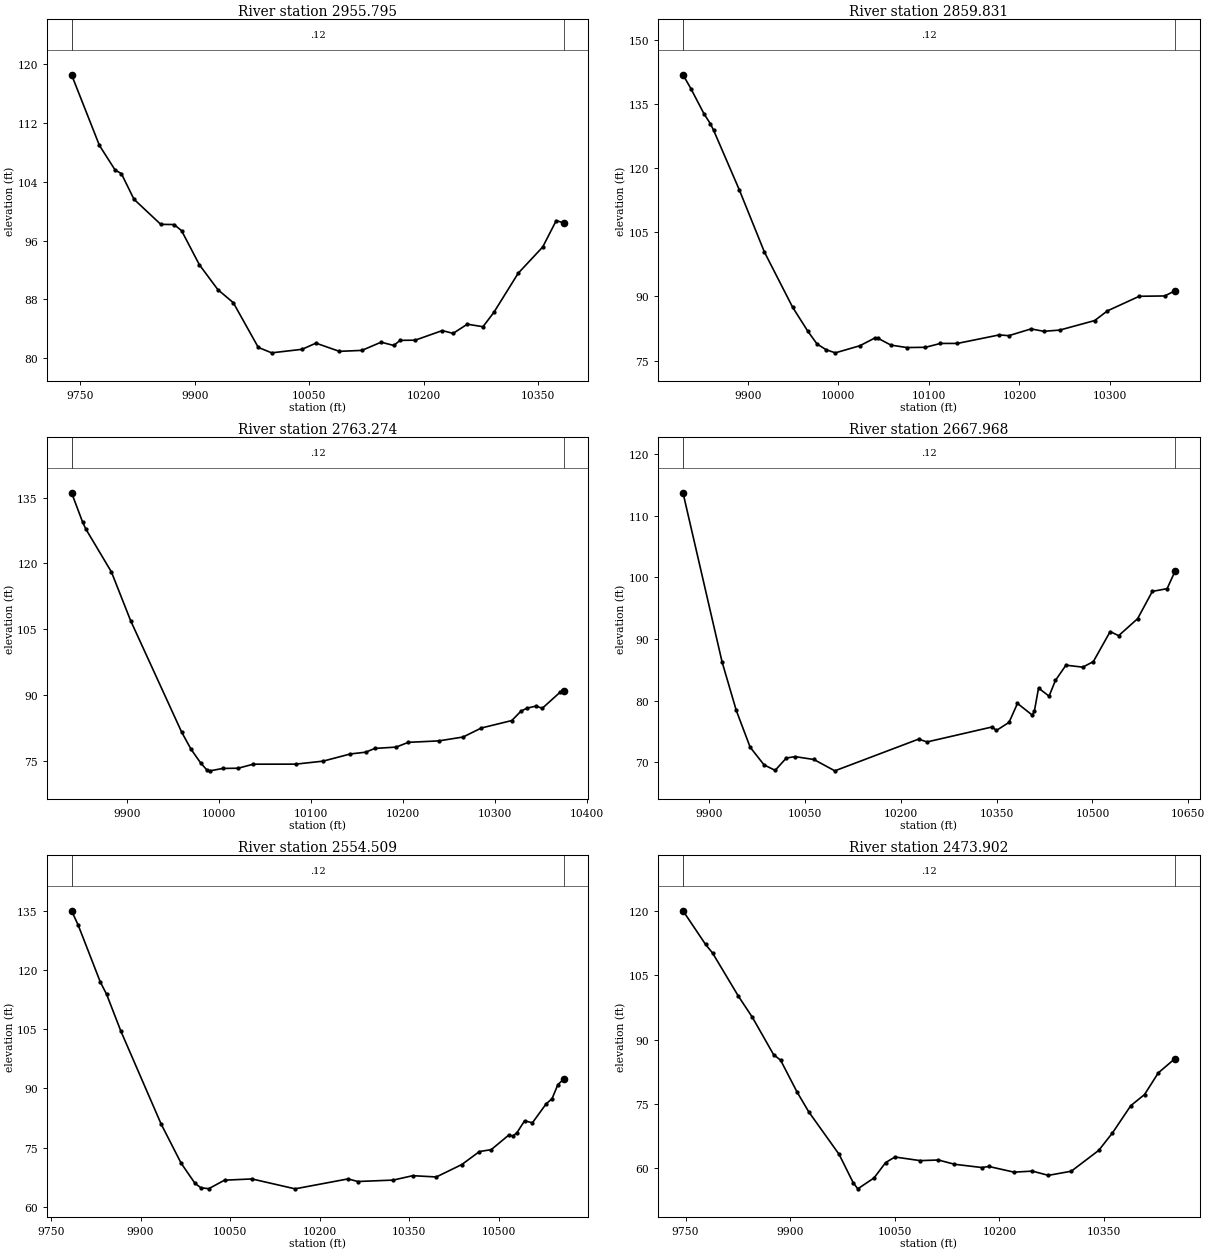
Type RM Length L Ch R = 1 ,2955.795,95.963200,95.963200,95.963200
XS GIS Cut Line= 6
 1246539.9864302837543.9993070661246423.85323435837449.080191225
1246375.67081189837396.7640716731246327.28530324837326.060594246
1246222.26728252 837239.485012711246036.27619317837161.276746616
#Sta/Elev= 30
9738.357118.57939774.861108.9664 9795.46105.6153  9803.7 105.124 9820.18101.6377
9855.31298.220319872.77998.194849882.631 97.35749905.958 92.72029930.23689.32855
9950.46987.555379983.19381.4725710000.7680.7322610040.5681.2122710058.8282.05175
10089.5280.9347910119.0981.0667610144.2482.1813310160.8881.7379310169.2482.43175
10188.8882.4537910224.4783.75949 10238.783.3819910257.2984.6310110277.8584.28527
10292.0986.2352310324.1291.5789610356.1595.1341110373.9598.7357610383.46 98.4221
#Mann= 3 , 0 , 0
9738.357    0.12       09738.357    0.12       010383.46    0.12       0
#XS Ineff= 2 , 0
       09941.849         10092.4       0
Bank Sta=9738.357,10383.46
Exp/Cntr=0.3,0.1

Type RM Length L Ch R = 1 ,2859.831,96.557300,96.557300,96.557300
XS GIS Cut Line= 6
1246551.78008932837334.9023812261246437.66730693837291.573664233
1246349.27435705837271.1013488921246313.40957913837257.336353421
1246259.88598797837228.2719184911246044.34766313837145.967140138
#Sta/Elev= 30
9828.631141.86059837.376138.61739851.625132.80049858.749130.44179862.312128.9366
9890.836114.91349918.499100.3807 9949.6587.466599966.498 81.82889976.58778.86943
9986.67777.519939996.76676.8007110023.7478.4522510040.6180.2978810044.0880.18009
10058.1478.6103810075.7178.0385410096.2478.0967110112.7879.0015310131.4579.00239
10177.6680.99611 10188.280.8174810212.7882.4006610226.8381.8375310244.39 82.1224
10283.02  84.35410297.07 86.623310332.1890.0334110360.2890.1109410371.5591.31107
#Mann= 3 , 0 , 0
9828.631    0.12       09828.631    0.12       010371.55    0.12       0
#XS Ineff= 2 , 0
       0                10111.49       0
Bank Sta=9828.631,10371.55
Exp/Cntr=0.3,0.1

Type RM Length L Ch R = 1 ,2763.274,95.306400,95.306400,95.306400
XS GIS Cut Line= 6
1246558.33282989837237.0834802991246473.68870735837207.395018712
1246417.33133918837189.1994570491246397.59424177837182.891334191
1246313.87891313837175.9150567951246035.23307979837139.456723481
#Sta/Elev= 30
9840.052136.08019852.055129.39499855.532127.82619883.346118.05599904.207106.9762
9959.58381.625999969.92677.667359980.26974.580249987.16472.941099990.59572.76152
10004.3873.3093310021.0873.3558910037.5474.2748810083.6474.2859310113.3674.96931
10143.1476.6103310159.6977.0073310169.6177.8651210192.7878.1654710206.0179.24889
 10239.179.5807710265.5780.4623310285.4282.5166410318.5184.2134810328.4486.33962
10335.0587.0380810344.9887.51241 10351.686.9941110371.4590.7424510374.7290.91579
#Mann= 3 , 0 , 0
9840.052    0.12       09840.052    0.12       010374.72    0.12       0
#XS Ineff= 2 , 0
       0                10144.62       0
Bank Sta=9840.052,10374.72
Exp/Cntr=0.3,0.1

Type RM Length L Ch R = 1 ,2667.968,113.458900,113.458900,113.458900
XS GIS Cut Line= 6
1246558.41884369837148.4410984811246480.29384369837115.889015138
1246448.00077459837100.3287826931246401.08377421 837083.33693181
 1246139.5820381837089.8473484671245803.21051037837126.739709571
#Sta/Elev= 30
9858.797113.74759920.05486.276619942.24678.422029963.94372.460589985.69169.58899
10003.1468.6931610020.5870.6913310034.2370.9249910063.7670.4580310096.5868.61615
10227.8673.7663910240.9873.3060410343.0175.7397910349.6275.1694810369.4276.48491
10382.6279.5586210405.7277.6703110409.0378.2731810415.63 82.048410432.1380.73404
10442.0383.2826110458.5385.7656410484.9485.4447310501.4486.3474410527.8491.22338
10541.0590.5518310570.7593.3104110593.8597.7426310616.9698.18381 10629.2100.9723
#Mann= 3 , 0 , 0
9858.797    0.12       09858.797    0.12       0 10629.2    0.12       0
#XS Ineff= 2 , 0
       0                10213.98       0
Bank Sta=9858.797,10629.2
Exp/Cntr=0.3,0.1

Type RM Length L Ch R = 1 ,2554.509,80.607200,80.607200,80.607200
XS GIS Cut Line= 6
1246682.36359559837045.6391301291246523.96385498837004.806498287
1246475.98171519836996.2568773911246447.18900202836994.289210467
1246268.74002422837002.5209595841245865.09419088 837026.39248736
#Sta/Elev= 30
 9784.38134.93969795.453131.31549832.538116.90759843.048113.81759866.846104.5265
9934.40780.984689967.89471.077719991.22265.9544110001.1664.8484510014.31 64.6231
10040.6166.7751310086.5967.0874110158.8464.5825210247.5567.0972610263.9866.43865
10323.1466.7959610356.0167.9094810395.4567.5885210438.1770.7276310467.7574.01979
10487.4774.4990610517.05 78.212210523.6277.95972 10530.278.7039610543.3481.79275
10556.4981.2922310579.4986.0871610589.3587.3909610599.2190.9770410608.5792.27632
#Mann= 3 , 0 , 0
 9784.38    0.12       0 9784.38    0.12       010608.57    0.12       0
#XS Ineff= 2 , 0
       0                10278.38       0
Bank Sta=9784.38,10608.57
Exp/Cntr=0.3,0.1

Type RM Length L Ch R = 1 ,2473.902,159.525100,159.525100,159.525100
XS GIS Cut Line= 6
1246735.95989603836973.2757494751246552.82284048836931.538043573
1246489.24853331836918.8832159791246481.36109945836917.409534335
1246435.61043748836910.0620072631246037.62023255836894.014015138
#Sta/Elev= 30
9746.345120.00099778.626 112.1849788.721110.16959825.735100.12229845.92595.16188
 9876.2186.496729886.30585.195739909.85977.793299926.68473.157539970.21663.25101
9990.287  56.6889996.97755.2277110020.2957.76887 10036.961.3480810050.1962.64417
10086.3561.8032310112.6261.94341 10135.660.95342   1017560.1873710184.85 60.4415
10220.9759.1136410247.2459.3563410270.2258.3686810303.0659.3307510342.4664.19044
10362.16  68.26310388.4374.6080710408.1377.1997210427.8382.2431710451.67 85.5536
#Mann= 3 , 0 , 0
9746.345    0.12       09746.345    0.12       010451.67    0.12       0
#XS Ineff= 2 , 0
       0                10289.18       0
Bank Sta=9746.345,10451.67
Exp/Cntr=0.3,0.1

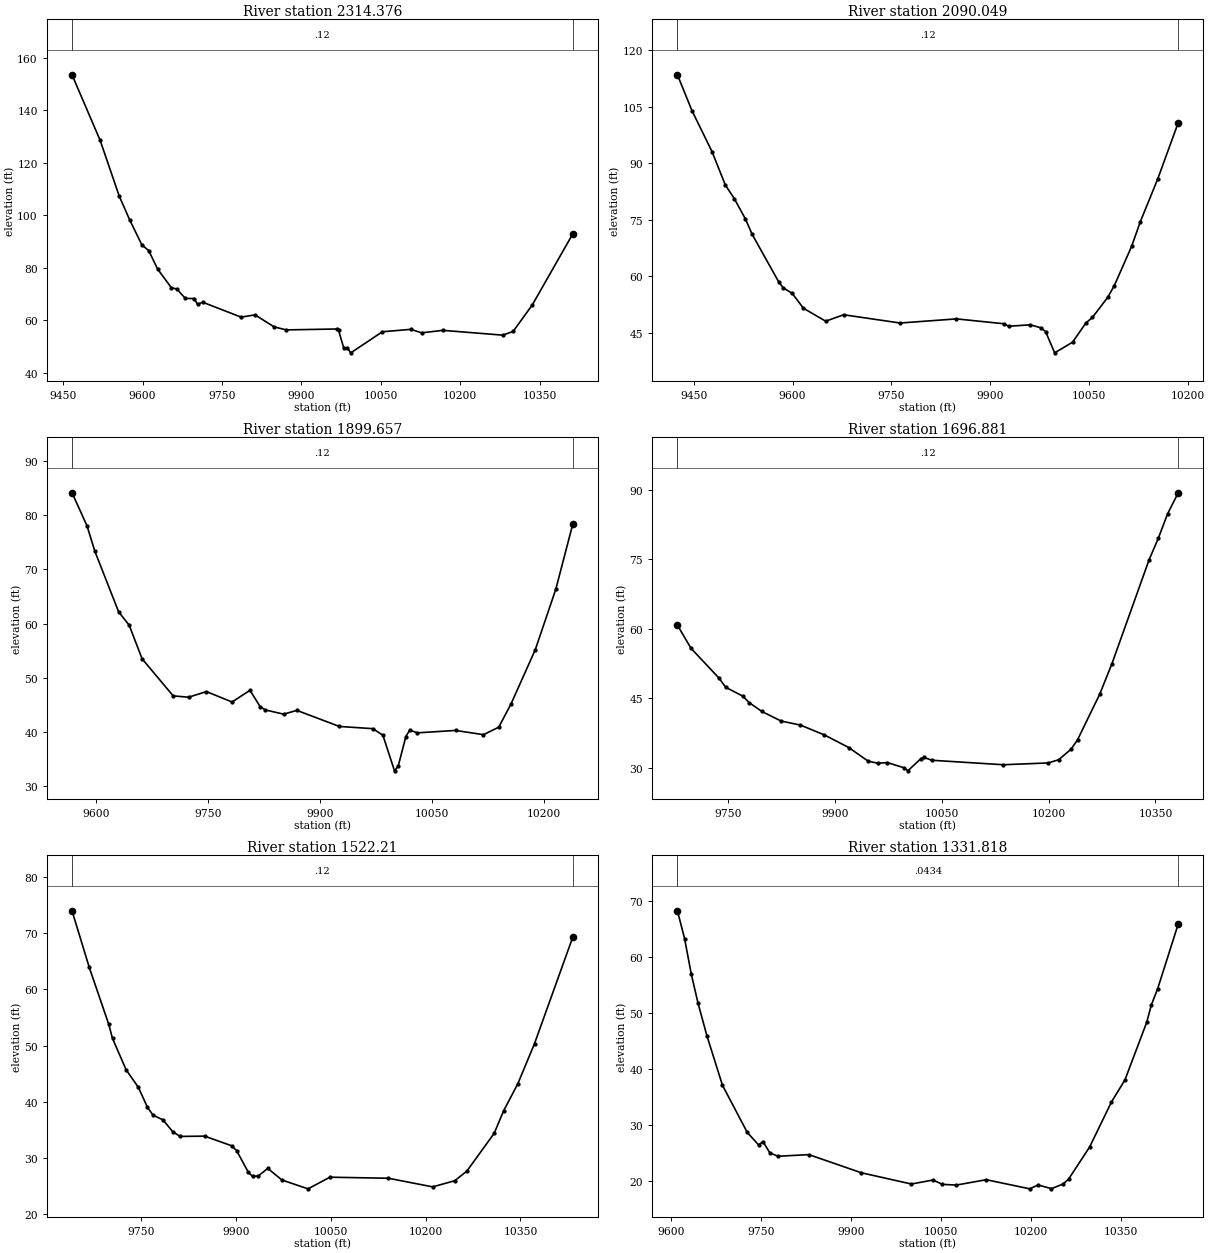
Type RM Length L Ch R = 1 ,2314.376,224.327500,224.327500,224.327500
XS GIS Cut Line= 6
1247052.64152649836798.6962480841246538.56062606836766.192834586
1246463.90784833836776.6095012581246272.87553337836814.523073509
1246190.07317835836817.1803826091246112.87192515 836811.19278127
#Sta/Elev= 30
9466.851153.5721 9519.84128.64219556.004107.3242 9575.7398.265249598.74388.75402
9611.89386.491949628.33179.561889654.63272.355529664.49571.951799680.93368.32399
9697.37168.273439703.94666.058889713.80966.859729786.13661.190889812.43762.05326
  9848.6 57.46969871.61256.321149966.92556.671319970.21256.117519980.07249.36874
9986.68249.479989993.308 47.579310052.9355.6199510106.6956.5300410126.8755.20623
 10167.256.1518510280.0454.3247110299.7455.7181710335.8465.7895210412.5992.97277
#Mann= 3 , 0 , 0
9466.851    0.12       09466.851    0.12       010412.59    0.12       0
#XS Ineff= 2 , 0
       09960.831        10309.37       0
Bank Sta=9466.851,10412.59
Exp/Cntr=0.3,0.1

Type RM Length L Ch R = 1 ,2090.049,190.392000,190.392000,190.392000
XS GIS Cut Line= 6
1246934.98097298836682.452998832 1246682.4408344836616.670265123
1246443.72555661836602.5643623621246392.65899137 836608.23842518
1246304.70523649836629.1867850271246187.71287358836632.332428113
#Sta/Elev= 30
9425.472113.49219447.418103.99959477.86293.099159498.15884.180479511.688 80.6051
9528.60175.180729538.74971.109829579.341 58.36789586.10656.863339599.63655.39876
9616.54951.445369650.37648.017319677.43749.732389763.14847.536689848.59948.63379
9920.90347.333749927.48446.670659960.49447.057529976.99946.241639983.809 45.2185
9997.43839.6117510024.6342.4348810044.7247.5378710054.7449.0142510077.9854.37592
10087.8657.4592110114.1967.9215410127.3574.4641710153.6185.7563610184.83 100.768
#Mann= 3 , 0 , 0
9425.472    0.12       09425.472    0.12       010184.83    0.12       0
#XS Ineff= 2 , 0
       09865.676                       0
Bank Sta=9425.472,10184.83
Exp/Cntr=0.3,0.1

Type RM Length L Ch R = 1 ,1899.657,202.776300,202.776300,202.776300
XS GIS Cut Line= 6
1246857.56308815836632.1616255941246609.63025761836546.829525977
1246550.69249672836521.6382290571246508.03118917836493.464866862
 1246390.9289102836396.6276890041246275.34355107836314.232849419
#Sta/Elev= 30
9567.40484.116359587.44678.046779598.07273.320749629.95262.166179644.01359.72926
9661.38853.523569703.04246.690879723.644 46.4445 9747.68 47.47929782.01645.55963
9806.05247.716739819.78744.686479826.65444.099569851.10643.323779868.96644.01545
 9925.8841.057989970.92240.647269984.351 39.42549999.86732.8767110004.8833.78004
10015.13 39.200210020.2640.3862910030.5539.8798210081.7840.31958 10119.239.54043
10139.6440.9192610155.9945.1638710188.6855.2037510216.2166.3593910239.0378.38347
#Mann= 3 , 0 , 0
9567.404    0.12       09567.404    0.12       010239.03    0.12       0
#XS Ineff= 2 , 0
       09919.719        10092.61       0
Bank Sta=9567.404,10239.03
Exp/Cntr=0.3,0.1

Type RM Length L Ch R = 1 ,1696.881,174.670800,174.670800,174.670800
XS GIS Cut Line= 6
1246813.46291491836521.8512777541246587.83077648836308.154167682
1246578.31389362836295.6408742071246561.06116876 836277.67036666
1246383.61199373836115.5591073191246299.52689606836042.857816637
#Sta/Elev= 30
9679.11260.791489698.16355.774629737.30149.364519746.843 47.35039770.46345.46402
9780.24143.998239797.57642.116249824.68840.048419851.801 39.17319885.20637.05368
9919.58234.319349946.69531.388979960.25130.927279973.80731.062259997.70129.92209
 10002.529.2819410020.3731.8560710024.9232.1960210036.2231.5692110136.4130.60213
10199.6430.9903910214.2331.6831510231.7433.9831410240.6335.9799410271.72 45.8183
10289.0752.4847310341.1174.9181710354.1279.5864310367.1384.8783910382.0289.40018
#Mann= 3 , 0 , 0
9679.112    0.12       09679.112    0.12       010382.02    0.12       0
#XS Ineff= 2 , 0
       09927.979        10208.53       0
Bank Sta=9679.112,10382.02
Exp/Cntr=0.3,0.1

Type RM Length L Ch R = 1 , 1522.21,190.391900,190.391900,190.391900
XS GIS Cut Line= 6
1246906.05194554 836501.645670221246756.70586309836265.464042798
1246690.85080859836140.1618440451246662.56236219836117.531086907
1246468.55194554835996.4373368921246376.10402882835944.354003564
#Sta/Elev= 30
9640.64273.98087 9667.9663.892179698.57553.842599704.71351.264049726.18545.70084
9745.59442.570549759.96239.026929768.88437.614599784.51736.783099799.93834.69297
9811.58333.838969850.40133.89265  9893.132.179049901.15231.298099919.56827.45095
9926.28926.730349935.26526.804479950.26528.152289972.76526.0854410013.9424.51581
10048.6426.5864210141.2126.39775 10211.124.8653510245.9125.9531910265.13 27.6529
10308.51 34.400410323.2638.3640510345.9443.22596 10372.350.36145 10432.969.32815
#Mann= 3 , 0 , 0
9640.642    0.12       09640.642    0.12       0 10432.9    0.12       0
#XS Ineff= 2 , 0
       0 9946.76                       0
Bank Sta=9640.642,10432.9
Exp/Cntr=0.3,0.1

Type RM Length L Ch R = 1 ,1331.818,190.392000,190.392000,190.392000
XS GIS Cut Line= 6
1247040.60055664836453.034559101 1246929.9783631836244.920925751
 1246907.0515371836192.6006263791246865.81470099836077.456581444
1246822.71861219836010.7602535491246588.34361216835764.666503564
#Sta/Elev= 30
9610.84268.319119622.80263.323659633.94256.984189645.08151.814679659.93445.94897
9685.92737.061869727.14128.635469745.98426.398979753.521 26.97139764.82724.96813
9778.47724.353339829.90224.647679917.07721.4030310000.6119.3847110036.7520.09732
10052.3719.3193310075.4419.1944210125.4420.1542310197.93 18.519610211.5319.21056
10234.0618.5598110253.0919.36122 10262.620.2613210297.6126.0087710333.9634.06596
10356.5138.0337510392.7548.3454710400.56 51.488210410.8854.3160110445.2865.95917
#Mann= 3 , 0 , 0
9610.842  0.0434       09610.842  0.0434       010445.28  0.0434       0
#XS Ineff= 2 , 0
       09885.332                       0
Bank Sta=9610.842,10445.28
Exp/Cntr=0.3,0.1