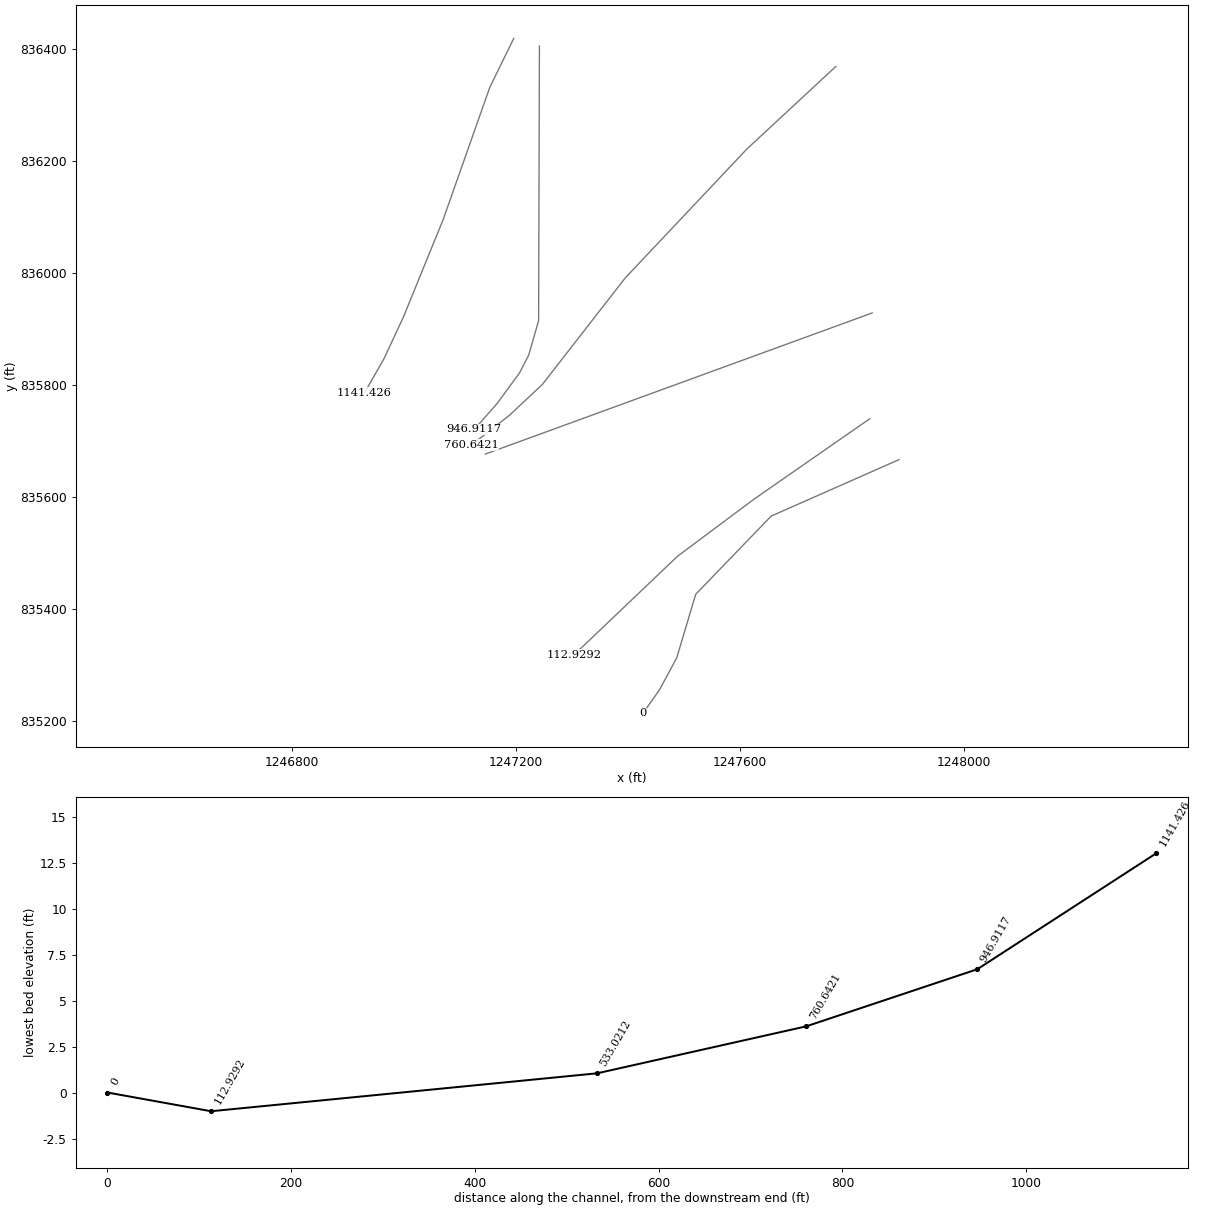
HEC-RAS study 84_ras.prj: 84

--- 84_ras.g01 (geometry) --- (continued)

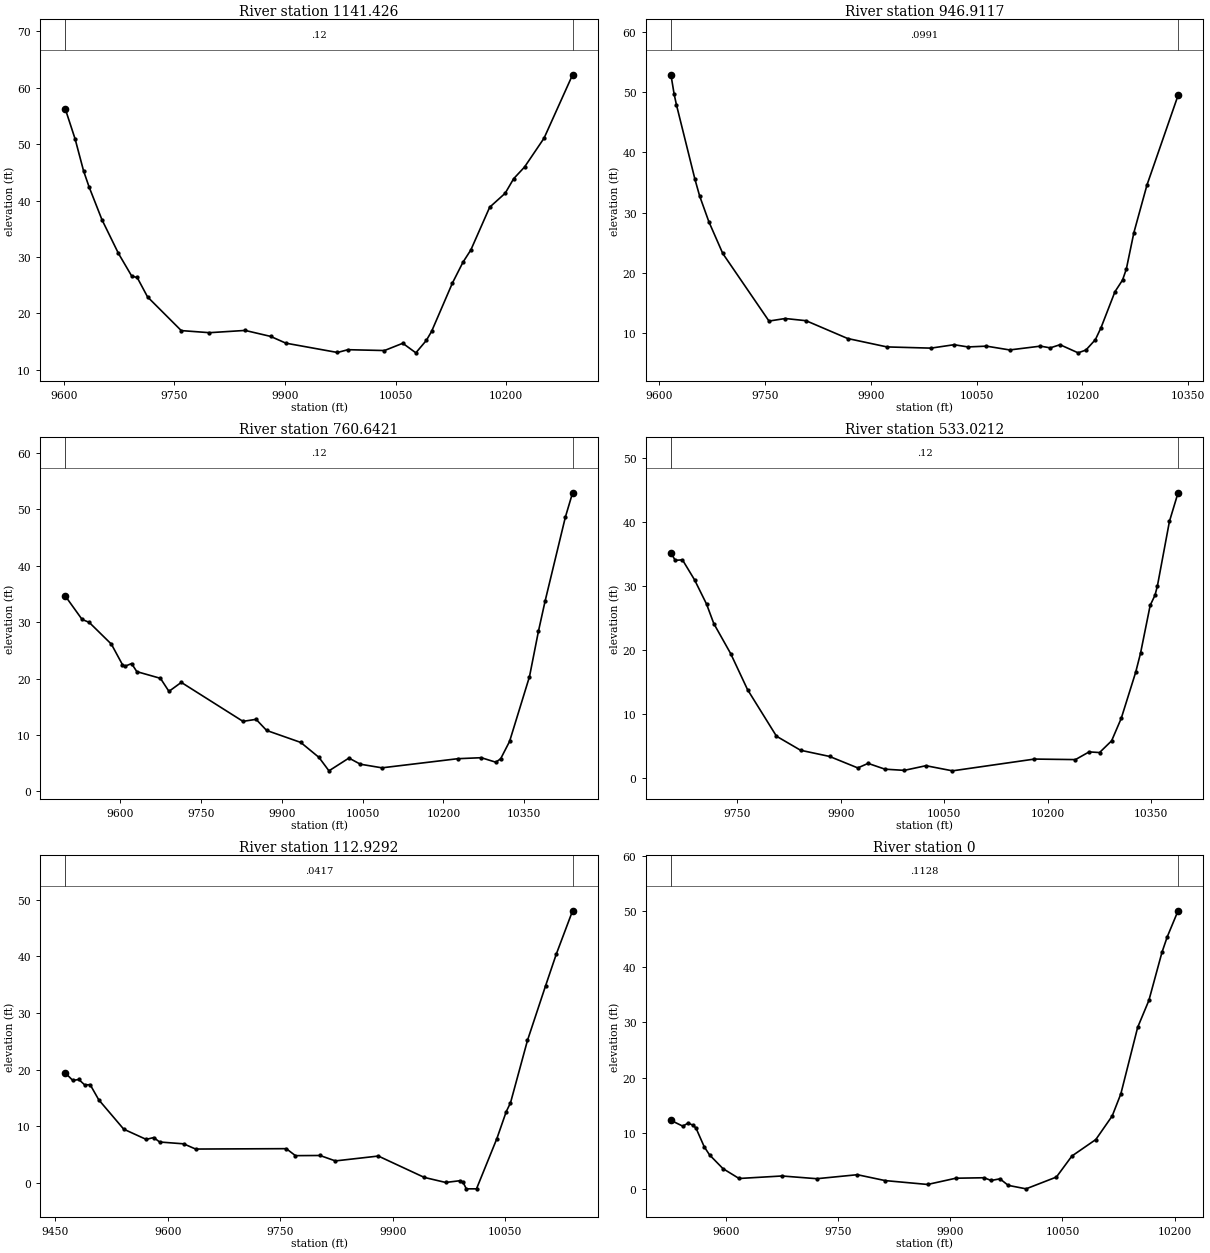
Type RM Length L Ch R = 1 ,1141.426,194.514300,194.514300,194.514300
XS GIS Cut Line= 6
1247196.19489199836418.2676421111247153.37499949836330.682672352
1247070.19300213836094.7810791881246999.17761979835920.720182389
1246964.52895698835846.4253532591246929.70985436835785.463405773
#Sta/Elev= 30
9602.23856.15201 9615.3550.908519626.83945.242879634.26742.424119651.73636.61082
9674.16730.619369692.26226.58491  9699.5 26.3711 9713.5822.925769759.318 16.9523
9797.57516.58116 9845.9316.981719880.46915.925319901.19214.722949971.23813.07055
9985.36113.5655710034.9513.4173310059.7914.7046910077.5313.0087110091.7215.20697
10098.8216.7936910127.2125.4060910141.4729.07981 10152.131.2416910177.6738.82207
10198.6841.2979110210.2543.8879810224.9545.9486810251.3951.0568910290.1462.30037
#Mann= 3 , 0 , 0
9602.238    0.12       09602.238    0.12       010290.14    0.12       0
#XS Ineff= 2 , 0
       09829.903                       0
Bank Sta=9602.238,10290.14
Exp/Cntr=0.3,0.1

Type RM Length L Ch R = 1 ,946.9117,186.269600,186.269600,186.269600
XS GIS Cut Line= 6
1247241.98944551836404.4234480111247240.53298229835914.603448004
1247222.89783686835853.0981310761247206.58982423835821.528322443
1247166.63081065835766.8444790691247125.67000109835720.395670235
#Sta/Elev= 30
9616.24652.891839620.85349.643439624.13447.87168 9650.3835.505339656.94232.77496
9670.06528.48734 9689.7523.223249755.36711.992469778.33312.41707 9807.8612.05483
9866.9289.0966829922.7237.699268 9985.097.49794910017.928.06527110037.627.696033
10063.88 7.8280610096.767.19715710140.487.82954110154.337.54157910168.198.065328
10193.89 6.7164810204.977.18423710218.37 8.9088510226.4210.9112310246.1516.87151
10256.8818.8033810262.2520.6249410272.9826.6824210291.5234.5779810335.6549.47198
#Mann= 3 , 0 , 0
9616.246  0.0991       09616.246  0.0991       010335.65  0.0991       0
#XS Ineff= 2 , 0
       09819.095                       0
Bank Sta=9616.246,10335.65
Exp/Cntr=0.3,0.1

Type RM Length L Ch R = 1 ,760.6421,227.620900,227.620900,227.620900
XS GIS Cut Line= 6
1247770.74327314836367.9876251971247612.11631596836220.790894121
1247395.34533766835991.0300279261247247.15981936835800.681583241
1247189.06946385835746.1515262721247120.46166775835692.617892444
#Sta/Elev= 30
9499.03734.592869529.82330.488749543.024 29.96399584.19526.096739604.63222.47516
9609.03322.163239621.64222.64746 9631.4221.217899675.20820.030259690.96517.71649
9713.86619.310639828.26312.394049852.60612.755859872.08110.783849935.373 8.65661
9969.2215.9984959987.7393.61328410024.795.880674   100464.790013   10086 4.14756
10226.745.76790510270.235.94490210297.245.14338710306.245.76661510322.688.827614
10359.6620.3351510376.3128.4106610388.6533.7527610426.2448.65878 10439.652.96037
#Mann= 3 , 0 , 0
9499.037    0.12       09499.037    0.12       0 10439.6    0.12       0
#XS Ineff= 2 , 0
       09917.066                       0
Bank Sta=9499.037,10439.6
Exp/Cntr=0.3,0.1

Type RM Length L Ch R = 1 ,533.0212,420.092000,420.092000,420.092000
XS GIS Cut Line= 2
1247835.64794183835928.2685406211247145.54377514835676.532429501
#Sta/Elev= 30
9654.14735.122339660.35933.948829670.83634.027189688.29730.915839705.75927.11306
9716.23624.069249740.68219.378259765.12813.747019807.0356.4715579841.9584.275622
9883.8663.3127549924.814 1.517419939.7432.2270289964.1891.3202469992.1271.135444
10023.561.86260710061.971.06079510180.712.89981410240.082.81708610259.894.020207
   102753.91905910292.475.75129210306.439.26400310327.3916.4803910334.3719.43945
10348.3426.9168410355.3328.5008210358.8229.9565710376.2840.0538910388.7344.50428
#Mann= 3 , 0 , 0
9654.147    0.12       09654.147    0.12       010388.73    0.12       0
#XS Ineff= 2 , 0
       09892.194                       0
Bank Sta=9654.147,10388.73
Exp/Cntr=0.3,0.1

Type RM Length L Ch R = 1 ,112.9292,112.929200,112.929200,112.929200
XS GIS Cut Line= 4
1247831.30766404835739.4664572781247625.14446956835596.237290606
1247488.42571959835494.2407628451247303.96391401 835318.45951283
#Sta/Elev= 30
9463.30219.403269473.11218.111949481.10218.277539489.09217.311089496.22117.37076
9507.721 14.69439541.0269.5192419570.9747.7176879580.9758.0420299588.9647.258281
9620.9236.9353319636.9036.0165269757.7946.0828119770.0744.851854 9802.824.881222
9823.2863.9233429880.5914.7819839941.8821.0158149970.417 0.12574 9989.440.433692
9993.4270.2030989997.959  -0.99910011.55  -0.99910038.757.87279510051.2612.62941
10056.8714.1561910079.53 25.171510103.5834.7594110117.8440.3381610139.7148.02292
#Mann= 3 , 0 , 0
9463.302  0.0417       09463.302  0.0417       010139.71  0.0417       0
#XS Ineff= 2 , 0
       09823.657                       0
Bank Sta=9463.302,10139.71
Exp/Cntr=0.3,0.1

Type RM Length L Ch R = 1 ,       0,0.000000,0.000000,0.000000
XS GIS Cut Line= 6
 1247883.6098637835666.5872715711247655.52641404835565.855346158
1247520.80733317835426.3140763491247487.03539997835313.110853255
1247456.26117989 835255.926509411247426.60073069835213.845494047
#Sta/Elev= 30
9526.49812.34244 9542.2711.300369549.44311.841669556.61611.438299560.20310.89299
9570.9627.6048339578.1366.1265389596.0683.6582219617.5881.8811929674.973 2.33227
9721.5981.8420769775.835 2.560819813.0451.5017129869.7280.8051199907.5171.930459
9945.3052.0137819954.752 1.521079966.4941.8205049977.589 0.6429410001.410.018402
10042.022.141286 10062.75.92075610094.67  8.887810116.6113.1322910128.1817.11584
10150.6729.0836210165.67 33.927510183.1742.5840210190.2545.3770110204.69 50.0575
#Mann= 3 , 0 , 0
9526.498  0.1128       09526.498  0.1128       010204.69  0.1128       0
#XS Ineff= 2 , 0
       09891.767                       0
Bank Sta=9526.498,10204.69
Exp/Cntr=0.3,0.1